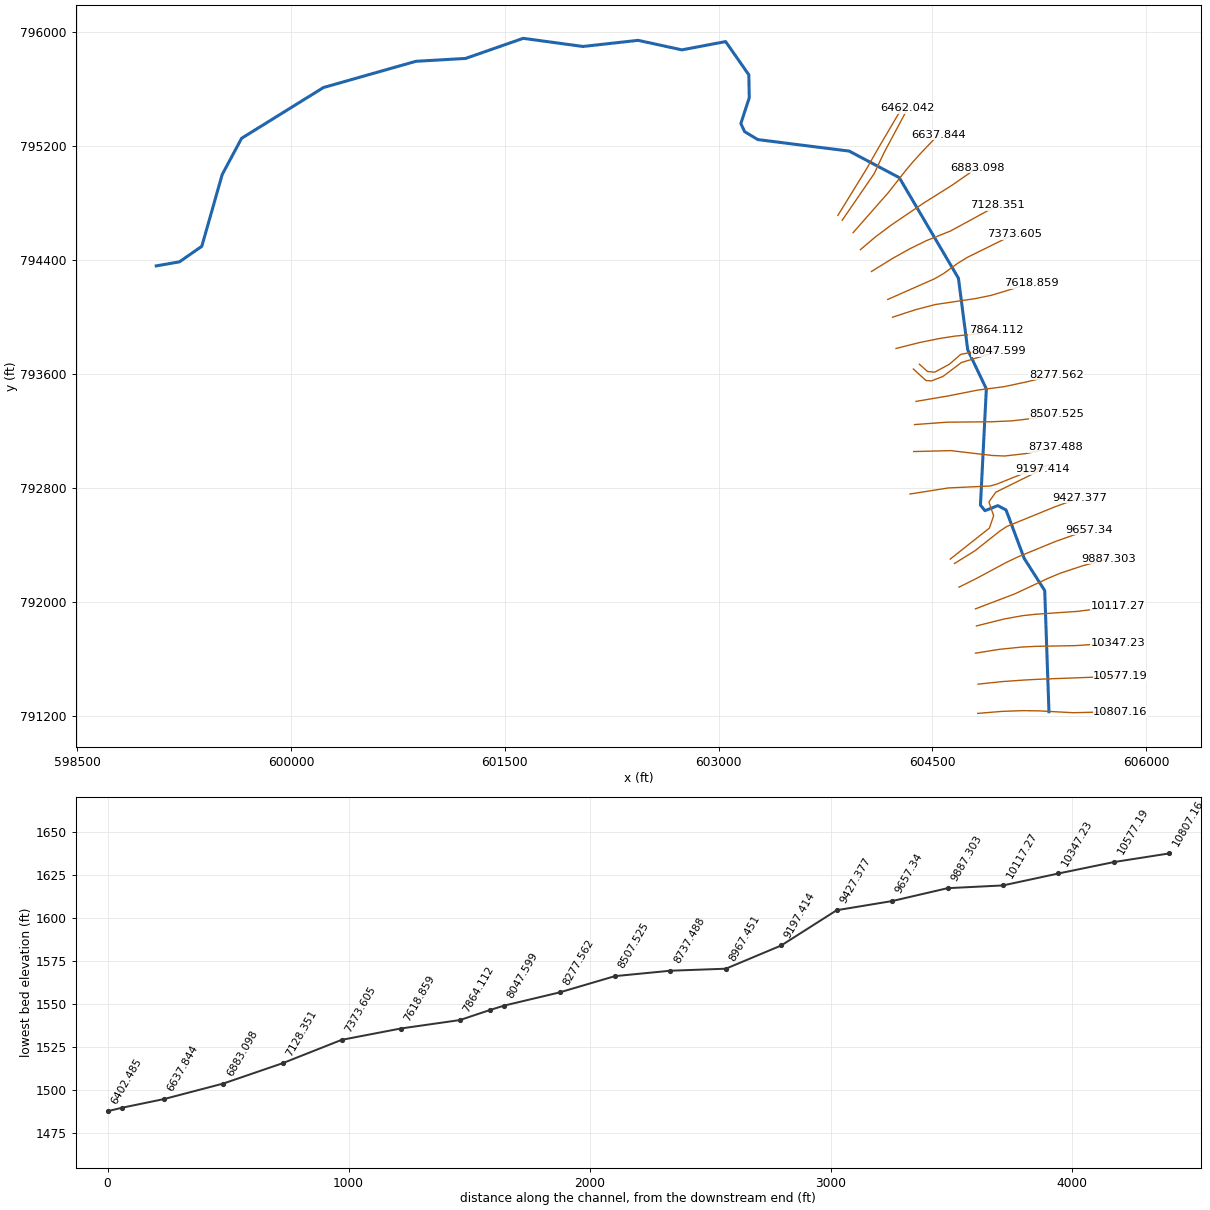
--- 10409_ras.prj (project) ---

Proj Title=10409
Current Plan=p01
Default Exp/Contr=0.3,0.1
English Units
Geom File=g01
Flow File=f01
Plan File=p01
Y Axis Title=Elevation
X Axis Title(PF)=Main Channel Distance
X Axis Title(XS)=Station
BEGIN DESCRIPTION:
RFD model 10409 exported to HEC-RAS
END DESCRIPTION:

--- 10409_ras.p01 (plan) ---

Plan Title=Plan 01
Program Version=4.10
Short Identifier=Plan 01
Geom File=g01
Flow File=f01
Subcritical Flow
Calc Critical at every XS
Secant Critical Depth

--- 10409_ras.f01 (steady flow) ---

Flow Title=Flow 01
Program Version=5.01
Number of Profiles= 6
Profile Names=10yr,25yr,50yr,100yr,100plus,500yr
River Rch & RM=10409,38,10807.16
 3021.65 4670.71 6180.36 7470.8210907.3912077.87
River Rch & RM=10409,38,10577.19
 3025.26 4676.62 6188.48 7480.9510922.1912093.07
River Rch & RM=10409,38,10347.23
  3179.6 4928.47 6533.52 7910.5111549.3512731.14
River Rch & RM=10409,38,10117.27
  3185.3 4937.85 6546.45 7926.6811572.9612755.32
River Rch & RM=10409,38,9887.303
 3291.35 5113.21 6788.64  8230.312016.2413210.49
River Rch & RM=10409,38, 9657.34
 3294.33 5118.15 6795.46 8238.8712028.7513223.32
River Rch & RM=10409,38,9427.377
 3348.14  5206.5 6916.97 8390.6612250.3613448.06
River Rch & RM=10409,38,9197.414
 3351.54 5212.12 6924.74 8400.41 12264.613462.63
River Rch & RM=10409,38,8967.451
  3354.3 5216.68 6931.06 8408.3312276.1713474.46
River Rch & RM=10409,38,8737.488
 3375.63 5252.05 6979.98 8469.7412365.8313566.23
River Rch & RM=10409,38,8507.525
 3380.92  5260.8 6992.08 8484.9412388.0113588.91
River Rch & RM=10409,38,8277.562
 3384.18 5266.26 6999.69 8494.5312402.0213603.42
River Rch & RM=10409,38,8047.599
 3418.03 5323.04 7078.77 8594.4112547.8413754.47
River Rch & RM=10409,38,7864.112
 3419.23 5325.06 7081.59 8597.9812553.0513759.89
River Rch & RM=10409,38,7618.859
 3425.02 5334.81 7095.21 8615.2112578.2113786.05
River Rch & RM=10409,38,7373.605
 3430.01 5343.21 7106.94 8630.0612599.8913808.58
River Rch & RM=10409,38,7128.351
 3467.54 5406.07 7194.42 8740.4612761.07 13974.9
River Rch & RM=10409,38,6883.098
  3560.9 5563.58 7414.64 9019.45 13168.414397.56
River Rch & RM=10409,38,6637.844
  3567.1 5574.08 7429.35 9038.1313195.6714425.91
River Rch & RM=10409,38,6462.042
 3569.39 5577.98 7434.83  9045.113205.8514436.54
River Rch & RM=10409,38,6402.485
 3574.45 5586.54 7446.81 9060.2913228.0314459.56
River Rch & RM=10409,38,6147.337
 3587.65 5608.98 7478.32 9100.3613286.5314520.57
River Rch & RM=10409,38,5985.425
 3590.88 5614.48 7486.05  9110.2 13300.914535.59
River Rch & RM=10409,38,5805.501
 3592.21 5616.74 7489.24 9114.2613306.8114541.77
River Rch & RM=10409,38,5734.154
 3592.78 5617.71  7490.6 9115.9913309.3514544.42
River Rch & RM=10409,38, 5547.11
 3653.31 5718.89 7631.32 9293.4813568.4914809.25
River Rch & RM=10409,38,5310.587
  3663.2 5735.69 7654.92  9323.513612.3114854.81
River Rch & RM=10409,38,5231.488
 3663.95 5736.98 7656.73  9325.813615.6714858.32
River Rch & RM=10409,38,5042.527
 3664.33 5737.63 7657.63 9326.9613617.3614860.07
River Rch & RM=10409,38,4809.613
  3689.2 5779.89 7716.99 9402.4613727.5914974.59
River Rch & RM=10409,38,4475.645
 3693.16 5786.64 7726.48 9414.5313745.2214992.92
River Rch & RM=10409,38,4185.308
 3699.71 5797.82 7742.21 9434.5813774.4915023.44
River Rch & RM=10409,38,3737.791
 3719.13 5830.86 7788.66  9493.7 13860.815113.14
River Rch & RM=10409,38,3640.009
 3719.69 5831.82 7790.01 9495.4213863.3115115.75
River Rch & RM=10409,38,2954.785
 3721.55    5835 7794.49 9501.1313871.6515124.44
Boundary for River Rch & Prof#=10409,38,1
Up Type= 0
Dn Type= 2
Boundary for River Rch & Prof#=10409,38,2
Up Type= 0
Dn Type= 2
Boundary for River Rch & Prof#=10409,38,2
Up Type= 0
Dn Type= 2
Boundary for River Rch & Prof#=10409,38,2
Up Type= 0
Dn Type= 2
Boundary for River Rch & Prof#=10409,38,2
Up Type= 0
Dn Type= 2
Boundary for River Rch & Prof#=10409,38,2
Up Type= 0
Dn Type= 2

--- 10409_ras.g01 (geometry) ---

Geom Title=10409
Program Version=4.10

River Reach=10409,38
Reach XY= 30
605317.990389168791229.859642908605288.213067323792079.712698713
605143.983485222792305.879357979605016.900151908792645.346950561
604959.261263013792675.555283904604868.983485222792640.138617232
604837.386263013792679.027506113604878.705707461793494.652506113
604748.150151998793768.541395023604682.872374117  794271.3191728
604267.941818565794976.701117232603916.639735311795162.899033904
603275.710915774795243.584797814603183.349804759795299.140353352
603156.266471356  795356.0847978603215.294249117795536.640353352
603212.516471356795697.751464456 603049.75605467795931.215006113
602742.898415864795873.055283904602435.606749207795939.895561665
602048.453971356 795896.92681168601629.305877447795953.988025874
601225.343855411795813.012966186600876.732744306 795792.87407732
600228.121633202795608.846299529 599653.81607765795252.596299514
599517.704966545794998.429632843599374.649410963794494.957410619
599217.704966635794385.929632857599055.204966545794357.457410619

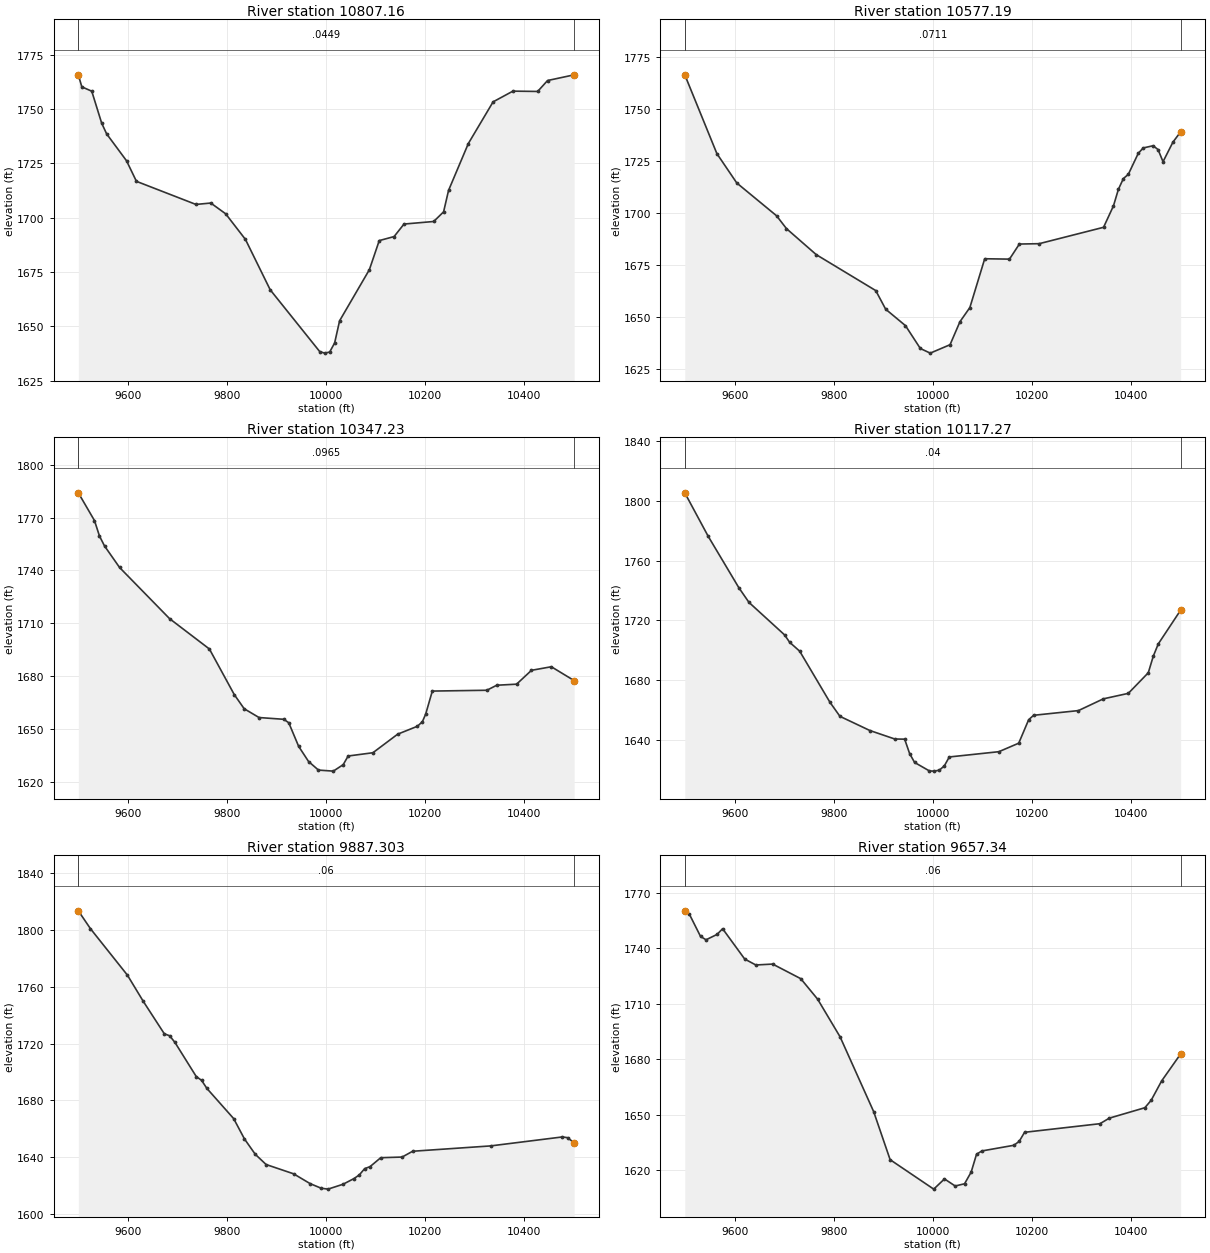
Type RM Length L Ch R = 1 ,10807.16,229.963100,229.963100,229.963100
XS GIS Cut Line= 6
604817.979320157 791218.16134483 604987.49648506791232.080164306
605131.069265767791237.267111708605245.469778904791235.835447547
605487.894763029791222.862178686605818.695097317791230.856374906
#Sta/Elev= 30
 9499.051765.7299506.0941760.2049526.1621758.2019546.2291743.4739556.262 1738.55
9596.3971726.1859616.4641716.7049736.685 1706.079766.7051706.7159796.7241701.769
9836.7371689.962 9886.741666.7889986.8821638.3159996.9051637.61910006.941638.121
10016.961642.29310026.991652.50610087.111676.01110107.121689.42610137.131691.281
10157.14 1697.0410217.141698.21910237.141702.66210247.151712.52710287.151734.112
10337.16 1753.2910377.191758.22810427.221758.08310447.241763.11310500.971765.737
#Mann= 3 , 0 , 0
 9499.05  0.0449       0 9499.05  0.0449       010500.97  0.0449       0
#XS Ineff= 2 , 0
       0                               0
Bank Sta=9499.05,10500.97
Exp/Cntr=0.3,0.1

Type RM Length L Ch R = 1 ,10577.19,229.963100,229.963100,229.963100
XS GIS Cut Line= 6
 604820.51445093791423.305183922604989.667780189791441.134277457
605149.874480989791452.414289138605274.418272917791458.820062333
605643.390418793 791472.39693414605820.500617361791481.679422248
#Sta/Elev= 30
9499.0191766.4549563.8621728.5549604.0831714.4299684.4791698.6579704.5291692.472
9764.6771679.9649884.9111662.6769904.9371653.726 9944.991645.8039975.0171634.819
9995.0311632.59210035.06 1636.6410055.071647.70810075.081654.508 10105.11677.992
10155.141677.80410175.151685.06110215.181685.23610345.281693.11710365.311703.436
10375.321711.43810385.341716.55410395.351718.60810415.381728.68410425.391731.283
10445.421732.34410455.431730.49310465.451724.66510485.471734.088   105011739.027
#Mann= 3 , 0 , 0
9499.019  0.0711       09499.019  0.0711       0   10501  0.0711       0
#XS Ineff= 2 , 0
       0                               0
Bank Sta=9499.019,10501
Exp/Cntr=0.3,0.1

Type RM Length L Ch R = 1 ,10347.23,229.963100,229.963100,229.963100
XS GIS Cut Line= 6
604802.858280054791640.651658978604970.808148858791667.506906765
605130.574417507791683.681944952605227.943108997791688.482087794
605501.639152643791693.390369953605800.987970607791713.017844057
#Sta/Elev= 30
9499.0231784.0729531.6311768.3219541.7771759.5069551.9221753.8999582.3581741.656
9683.4081712.5859763.9091695.3379814.092 1669.469834.154 1661.41 9864.191656.405
9914.2511655.4019924.2631653.4339944.2671640.0189964.2671631.4229984.2681626.546
10014.271625.95610034.271629.63610044.271634.54610094.281636.40210144.311646.944
10184.331651.45810194.331654.05410200.981658.37710214.36 1671.4410324.521671.902
10344.551674.75810384.66 1675.3610414.75 1683.2310454.871685.26210500.991677.389
#Mann= 3 , 0 , 0
9499.023  0.0965       09499.023  0.0965       010500.99  0.0965       0
#XS Ineff= 2 , 0
       0                               0
Bank Sta=9499.023,10500.99
Exp/Cntr=0.3,0.1

Type RM Length L Ch R = 1 ,10117.27,229.963100,229.963100,229.963100
XS GIS Cut Line= 6
604809.370904273791831.773261669605003.490386918791880.210324642
605131.972781055791903.563754222605228.899980928791913.909684584
605514.078340821791933.452647981605799.734361429791969.322008017
#Sta/Elev= 30
 9499.031805.3659546.2141776.3119608.2041741.8489628.7521731.9899700.6571710.239
9710.8521705.3129731.2431699.3139792.2881665.1569812.5411655.701    98731646.213
9923.2841640.535 9943.341640.4089953.3611630.7639963.3811624.8319993.4441619.121
10003.461619.01510013.48 1619.69 10023.51622.53210033.511628.49910133.72 1632.03
10173.861637.73210193.931653.45210203.961656.40610294.491659.55110344.831667.415
10395.291671.08710435.661684.88510445.751695.99710455.841704.19910500.991726.788
#Mann= 3 , 0 , 0
 9499.03    0.04       0 9499.03    0.04       010500.99    0.04       0
#XS Ineff= 2 , 0
       0                               0
Bank Sta=9499.03,10500.99
Exp/Cntr=0.3,0.1

Type RM Length L Ch R = 1 ,9887.303,229.963000,229.963000,229.963000
XS GIS Cut Line= 6
604802.028513685 791951.39441668605077.844210773792056.414450616
 605313.31967761792166.521867815605400.442913926792202.642541669
605554.340725819792253.532708988  605737.9321509792303.892597609
#Sta/Elev= 30
9499.0161813.6759523.5051801.0849598.1281768.356 9630.111749.9239672.7841726.953
9683.5411725.5769694.2981720.8469737.3261696.8119748.0821694.1249758.8391688.427
9812.9111667.1519834.7591652.7959856.6071641.9669878.4551634.7739934.0011628.224
9967.3841621.3039989.6391618.07210003.591617.41710033.911620.85210055.98 1624.85
 10066.81627.43610077.631631.86910088.451633.264 10110.11639.57810153.311640.031
10174.531644.12510332.011647.88810477.181654.22110487.551653.70710500.961650.077
#Mann= 3 , 0 , 0
9499.016    0.06       09499.016    0.06       010500.96    0.06       0
#XS Ineff= 2 , 0
       0                               0
Bank Sta=9499.016,10500.96
Exp/Cntr=0.3,0.1

Type RM Length L Ch R = 1 , 9657.34,229.963100,229.963100,229.963100
XS GIS Cut Line= 6
604686.590623223792103.613179733 604809.35451084792164.656062884
605016.966823076792276.224400436605101.525147354792316.552288584
605364.658683526792424.549049674605601.356809525792508.080692602
#Sta/Elev= 30
 9499.031760.3129508.422 1758.429530.7581746.5219541.9261744.6579564.262 1747.57
 9575.431750.6469620.1021734.2559642.5421731.049  9676.61731.5389733.3621723.649
9767.4191712.5899812.8291692.2269880.7241651.7929913.9621625.84110002.061609.934
10023.791615.45110045.391611.62510064.361612.82610077.751619.15910088.541628.774
10099.321630.56110164.041633.62810174.821635.75110185.61 1640.6410337.991645.289
 10356.91648.28810428.711653.91810441.521657.95710462.621668.39510500.991682.971
#Mann= 3 , 0 , 0
 9499.03    0.06       0 9499.03    0.06       010500.99    0.06       0
#XS Ineff= 2 , 0
       0                               0
Bank Sta=9499.03,10500.99
Exp/Cntr=0.3,0.1

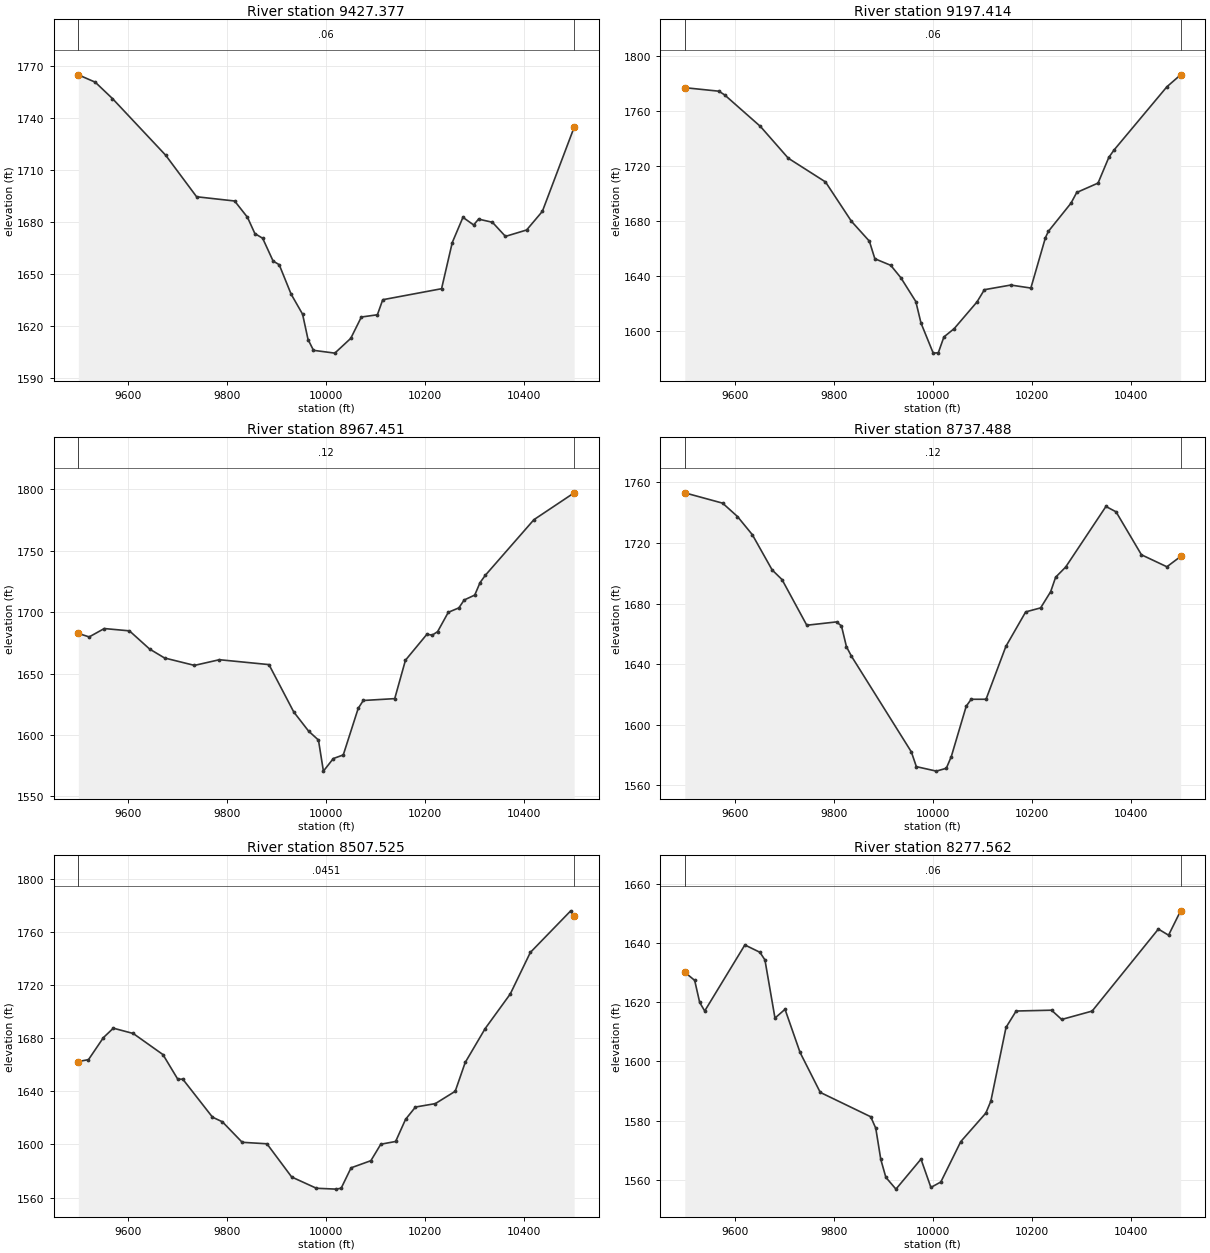
Type RM Length L Ch R = 1 ,9427.377,229.963100,229.963100,229.963100
XS GIS Cut Line= 6
 604655.52584184792269.800976221604800.265670052792359.953527914
604975.978500768 792499.21594838605022.972911713792529.703978334
 605358.80631373792666.876107518605535.587463717792731.361980594
#Sta/Elev= 30
9499.0731765.1729533.2171760.932 9567.971751.4979675.5671718.7919738.0521694.828
9814.9261692.3849840.8331682.9849855.8181673.587 9871.551670.8799892.6481657.749
9904.9881655.628 9929.051638.6539952.2141627.0799963.2431612.4759974.2721606.231
 10017.41604.61610049.551613.13910070.981625.444 10103.4 1626.75 10114.21635.426
10233.061641.77610254.661668.40310276.271682.96210297.881678.55410307.851681.933
10335.82  1680.110362.171671.96710404.921675.64910436.751686.40410500.991734.921
#Mann= 3 , 0 , 0
9499.073    0.06       09499.073    0.06       010500.99    0.06       0
#XS Ineff= 2 , 0
       0                               0
Bank Sta=9499.073,10500.99
Exp/Cntr=0.3,0.1

Type RM Length L Ch R = 1 ,9197.414,229.963100,229.963100,229.963100
XS GIS Cut Line= 6
604625.573846419 792300.71399642604900.262390273792518.239074804
604929.915101582792604.618017925604896.703573908792701.580575853
604944.826711158792769.567815889605271.066130504792930.808816187
#Sta/Elev= 30
9499.2331777.2529568.0661774.6939579.8471771.9539652.0151749.0329708.3091725.919
 9783.421708.6749835.8991680.0149872.006  1665.69883.1121652.793 9915.151648.021
9935.5081639.0519965.8211621.6869976.329 1606.01   100011584.13210011.281584.402
 10022.61595.90610043.361601.95910089.391621.35810104.391630.28210157.671633.661
10198.241631.47810227.651668.14310233.591672.72110279.181693.18610290.861701.008
10333.921707.83710355.721726.56610366.351731.95310473.031777.92510500.72  1786.6
#Mann= 3 , 0 , 0
9499.233    0.06       09499.233    0.06       010500.72    0.06       0
#XS Ineff= 2 , 0
       0                               0
Bank Sta=9499.233,10500.72
Exp/Cntr=0.3,0.1

Type RM Length L Ch R = 1 ,8967.451,229.963100,229.963100,229.963100
XS GIS Cut Line= 6
604343.440640629792757.222894402604612.695629223792799.738992751
604906.633995931792813.420465672604954.876630906792827.664623145
605150.826120873792906.143119284605315.315083017792960.512757297
#Sta/Elev= 30
9499.0581682.6919520.9811679.8729551.4881686.6799602.3321684.799 9642.991670.037
 9673.241662.7299733.7391656.6889784.0771661.3119884.261 1657.339934.2621618.831
9964.2631603.2279984.2641595.9089994.2641570.62410014.271580.86910034.391583.805
10064.581621.72410074.831628.11910138.361629.63810160.031660.89710203.351681.998
10214.191681.32310225.021684.17110246.591699.90610267.981703.50310278.671709.917
10300.061713.93510310.751724.06410321.441730.03610419.621775.29610500.92 1797.15
#Mann= 3 , 0 , 0
9499.058    0.12       09499.058    0.12       010500.92    0.12       0
#XS Ineff= 2 , 0
       0                               0
Bank Sta=9499.058,10500.92
Exp/Cntr=0.3,0.1

Type RM Length L Ch R = 1 ,8737.488,229.963000,229.963000,229.963000
XS GIS Cut Line= 6
604368.760997745793055.003209409604629.222389967793061.485773222
604921.851698314793027.237992348605007.039521019  793023.8115743
605162.721757439793041.685271021605361.952382419 793086.70886621
#Sta/Elev= 30
 9499.041753.0929575.431 1746.289605.4911737.4519635.5181725.4599675.5221702.221
9695.5271695.8389745.5441665.7219805.651 1667.929815.6731665.202 9825.721651.504
9835.7721645.3089956.8321582.1419966.9371572.41210007.32 1569.4510027.471571.331
10037.551579.05810067.711612.30110077.731616.86310107.781616.881 10147.81651.733
10187.891674.52910218.081677.169 10238.31687.84410248.411697.41810268.631704.107
10350.051744.09510370.47 1740.5610421.79 1712.2110473.21  1704.310500.941711.089
#Mann= 3 , 0 , 0
 9499.04    0.12       0 9499.04    0.12       010500.94    0.12       0
#XS Ineff= 2 , 0
       0                               0
Bank Sta=9499.04,10500.94
Exp/Cntr=0.3,0.1

Type RM Length L Ch R = 1 ,8507.525,229.963100,229.963100,229.963100
XS GIS Cut Line= 6
604374.568082941793244.184730983604601.251110667793260.966888794
604920.440578943793264.235572143 605058.20319154793270.303136388
605218.765806305793289.068094131605371.790907239793318.258722363
#Sta/Elev= 30
9499.0171662.4439519.5411663.8739549.678 1680.479569.7681687.5769609.9211683.581
9670.0181667.6879700.0671649.0799710.0831649.1779770.1211620.5329790.1271617.037
9830.1331601.5979880.1331600.4729930.1331575.4589980.1331566.96410020.141566.311
10030.141567.00810050.141582.35410090.181587.739 10110.21600.14110140.231602.221
10160.251618.88210180.27 1628.1610220.441630.73510260.621640.03410280.791661.728
10321.171687.29910371.791713.30510412.391744.63710494.041775.99510500.971771.796
#Mann= 3 , 0 , 0
9499.017  0.0451       09499.017  0.0451       010500.97  0.0451       0
#XS Ineff= 2 , 0
       0                               0
Bank Sta=9499.017,10500.97
Exp/Cntr=0.3,0.1

Type RM Length L Ch R = 1 ,8277.562,229.963100,229.963100,229.963100
XS GIS Cut Line= 6
604385.339546659793406.878685711604612.436882617793445.455677041
604818.727522869793486.339916482605001.407727372793509.851161114
605163.867280364793544.372683032 605368.69308443793594.471370364
#Sta/Elev= 30
9499.0261630.0639518.9681627.3169529.1111619.8759539.2541616.9829620.4011639.273
 9650.831636.7919660.9741634.217 9681.261614.5829701.5471617.5569731.9891602.969
9772.7671589.5029874.7121581.2789884.9071577.4139895.1011566.8579905.2961560.834
9925.6851556.8499976.2851566.9769996.3531557.41710016.431559.27310056.711572.899
10107.371582.52110117.511586.57610148.121611.44410168.57 1616.9710240.131617.249
10260.581614.11810322.141616.95110455.971644.63310476.561642.56910500.95 1650.79
#Mann= 3 , 0 , 0
9499.026    0.06       09499.026    0.06       010500.95    0.06       0
#XS Ineff= 2 , 0
       0                               0
Bank Sta=9499.026,10500.95
Exp/Cntr=0.3,0.1

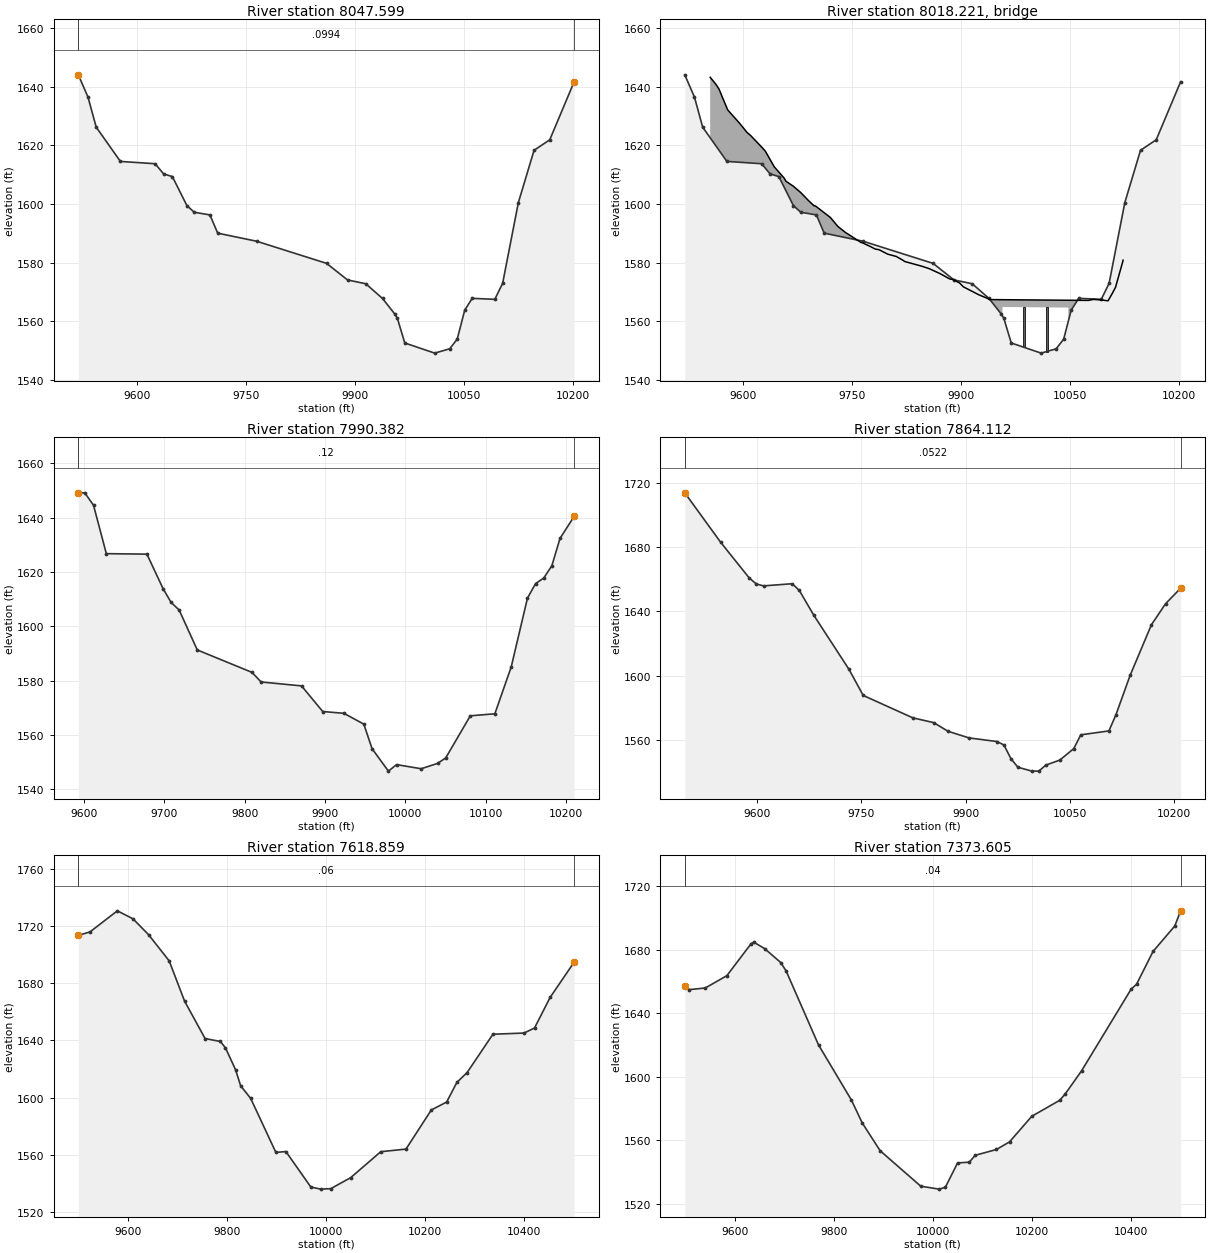
Type RM Length L Ch R = 1 ,8047.599,57.216700,57.216700,57.216700
XS GIS Cut Line= 6
604366.818452626793633.959917799604455.518721044793553.274733841
604493.456787705793550.603038996604574.676310629793582.129038036
604703.452001631793679.378729999604966.098484904793759.423737779
#Sta/Elev= 30
9519.7861644.0789533.102 1636.479544.3641626.2459577.6851614.5459625.4741613.761
 9637.131610.2969649.1981609.3729669.2481599.4559679.3811597.2129700.835 1596.31
9711.5621590.0869765.2381587.3279861.4111579.7839890.214 1574.139915.2551572.845
9938.4051567.8119955.5581562.3979958.793 1561.049968.9881552.64110010.121549.179
10030.791550.65610041.131553.94910051.461563.828 10061.81567.86210092.841567.524
10103.641572.98110125.251600.49510146.851618.34310168.451621.92110202.041641.724
#Mann= 3 , 0 , 0
9519.786  0.0994       09519.786  0.0994       010202.04  0.0994       0
#XS Ineff= 2 , 0
       0                               0
Bank Sta=9519.786,10202.04
Exp/Cntr=0.3,0.1

Type RM Length L Ch R = 3 ,8018.221,,,
BEGIN DESCRIPTION:
END DESCRIPTION:
Bridge Culvert--1,0,-1,-1, 0
Deck Dist Width WeirC Skew NumUp NumDn MinLoCord MaxHiCord MaxSubmerge Is_Ogee
15.485000,26.246700,2.6,0, 50, 50, , , 0.95, 0, 0,0,,
 9554.70 9562.71 9566.82 9578.76 9594.81 9605.17 9610.86 9626.92 9630.74 9642.97
 9656.30 9659.02 9669.03 9679.26 9689.49 9697.51 9699.72 9720.18 9730.42 9740.65
 9762.41 9763.85 9775.55 9781.67 9787.25 9798.95 9810.65 9820.19 9822.36 9845.76
 9855.87 9871.10 9884.50 9888.11 9897.90 9903.13 9924.71 9940.31 9956.97 9956.97
10047.5210047.5210075.2110081.7510091.9910102.2210107.4610112.4510122.6910122.84
 1643.24 1640.81 1639.24 1632.13 1627.66 1624.50 1623.26 1619.08 1617.99 1612.68
 1608.92 1607.78 1606.11 1603.95 1601.32 1599.45 1599.33 1595.42 1592.37 1590.36
 1586.88 1586.85 1585.48 1584.68 1584.44 1582.93 1582.15 1580.81 1580.42 1578.83
 1578.01 1576.28 1574.45 1574.33 1573.10 1571.78 1569.03 1567.44 1567.40 1567.40
 1567.21 1567.21 1567.16 1567.50 1567.33 1567.02 1569.30 1571.61 1580.62 1580.87
  643.24  640.81  639.24  632.13  627.66  624.50  623.26  619.08  617.99  612.68
  608.92  607.78  606.11  603.95  601.32  599.45  599.33  595.42  592.37  590.36
  586.88  586.85  585.48  584.68  584.44  582.93  582.15  580.81  580.42  578.83
  578.01  576.28  574.45  574.33  573.10  571.78  569.03  567.44  567.40 1564.90
 1564.71  567.21  567.16  567.50  567.33  567.02  569.30  571.61  580.62  580.87
 9554.70 9562.71 9566.82 9578.76 9594.81 9605.17 9610.86 9626.92 9630.74 9642.97
 9656.30 9659.02 9669.03 9679.26 9689.49 9697.51 9699.72 9720.18 9730.42 9740.65
 9762.41 9763.85 9775.55 9781.67 9787.25 9798.95 9810.65 9820.19 9822.36 9845.76
 9855.87 9871.10 9884.50 9888.11 9897.90 9903.13 9924.71 9939.62 9967.81 9967.81
10058.3610058.3610075.2110081.7510091.9910102.2210107.4610112.4510122.6910122.84
 1643.24 1640.81 1639.24 1632.13 1627.66 1624.50 1623.26 1619.08 1617.99 1612.68
 1608.92 1607.78 1606.11 1603.95 1601.32 1599.45 1599.33 1595.42 1592.37 1590.36
 1586.88 1586.85 1585.48 1584.68 1584.44 1582.93 1582.15 1580.81 1580.42 1578.83
 1578.01 1576.28 1574.45 1574.33 1573.10 1571.78 1569.03 1567.48 1567.38 1567.38
 1567.19 1567.19 1567.16 1567.50 1567.33 1567.02 1569.30 1571.61 1580.62 1580.87
  643.24  640.81  639.24  632.13  627.66  624.50  623.26  619.08  617.99  612.68
  608.92  607.78  606.11  603.95  601.32  599.45  599.33  595.42  592.37  590.36
  586.88  586.85  585.48  584.68  584.44  582.93  582.15  580.81  580.42  578.83
  578.01  576.28  574.45  574.33  573.10  571.78  569.03  567.48  567.38 1564.88
 1564.69  567.19  567.16  567.50  567.33  567.02  569.30  571.61  580.62  580.87
Pier Skew, UpSta & Num, DnSta & Num=  ,9986.65, 2 ,9997.49, 2 , 0 , 0 , 0 ,,
    3.00    3.00
  567.34 1567.34
    3.00    3.00
  567.32 1567.32
Pier Skew, UpSta & Num, DnSta & Num=  ,10017.84, 2 ,10028.68, 2 , 0 , 0 , 0 ,,
    3.00    3.00
  567.27 1567.27
    3.00    3.00
  567.25 1567.25
BR Coef=-1 , 0 , 0 ,, 0 ,,,0.8,0,1,0,
WSPro=,,,, 1 ,,,, 0 ,,,, 0 ,,,,-1 ,-1 ,-1 , 0 , 0 , 0 , 0 , 0
BC Design=,, 0 ,, 0 ,,,,,,

Type RM Length L Ch R = 1 ,7990.382,126.269900,126.269900,126.269900
XS GIS Cut Line= 6
604409.031230956793667.623272717604465.671161413793616.861070871
604516.433363259793612.052020162604618.492105901793667.088933736
604699.711628854793737.087338388604962.405866327793786.614838202
#Sta/Elev= 30
 9592.821649.1529600.8351649.1889611.734 1644.619627.6921626.7829678.249 1626.61
9698.3391613.9029708.3841608.8329718.4281606.0129740.9621591.3199809.1311583.063
9820.4921579.5259870.8151578.0889897.2181568.6469923.6211567.9859948.4361563.996
9958.6351554.9869979.0331546.6929989.2331549.08810019.831547.57110040.231549.534
10050.431551.55410081.031567.06110111.621567.81310131.991585.05110152.251610.411
10162.381615.77610172.511617.79110182.641622.34310192.771632.408 10210.41640.522
#Mann= 3 , 0 , 0
 9592.82    0.12       0 9592.82    0.12       0 10210.4    0.12       0
#XS Ineff= 2 , 0
       0                               0
Bank Sta=9592.82,10210.4
Exp/Cntr=0.3,0.1

Type RM Length L Ch R = 1 ,7864.112,245.253600,245.253600,245.253600
XS GIS Cut Line= 6
604245.085848391793778.406261563604413.167055786793820.539104074
 604554.01226896793848.873043284604660.012717783793865.080268115
 604811.96085304793880.585152388604946.027869195793907.216453537
#Sta/Elev= 30
 9495.841713.712 9547.461682.9819588.6481660.7749598.9451657.0369609.2421655.894
 9650.431657.2339660.7271653.0399681.2061637.8529732.2081603.9889752.6091587.826
9823.9191573.9139854.2671570.895  9874.51565.5729904.849 1561.439945.1431559.166
9955.1911557.0269965.239 1548.549975.2871543.2089995.3831540.78210005.431540.802
10015.491544.524 10035.61547.63710055.721554.78410065.781563.33210106.291565.772
10116.431575.84710136.791600.26510167.48 1631.7410187.941644.862 10209.51654.428
#Mann= 3 , 0 , 0
 9495.84  0.0522       0 9495.84  0.0522       0 10209.5  0.0522       0
#XS Ineff= 2 , 0
       0                               0
Bank Sta=9495.84,10209.5
Exp/Cntr=0.3,0.1

Type RM Length L Ch R = 1 ,7618.859,245.253700,245.253700,245.253700
XS GIS Cut Line= 6
604220.361775436793997.423752297604382.040713664794050.217215362
604521.029775218794086.520818931604799.998857643794127.835026308
604914.940256393794151.363557248605191.037530491794235.395926061
#Sta/Elev= 30
9499.0391713.6139522.6051716.0439577.8611730.8139609.4541725.2299640.8431714.154
9682.5831695.7779713.7111667.5829755.1811641.3439786.0361639.2979796.3211634.862
9816.8461619.4399827.0151608.2779847.3531599.3889898.1991561.5929918.4781562.201
9968.8561537.3389989.0071535.87710009.171536.19710049.521543.94910110.171562.096
 10161.11563.91110212.331591.33810243.321596.87310263.991610.64110284.721617.558
10336.821644.37610399.791645.20310420.861648.73610452.471670.19810500.971694.874
#Mann= 3 , 0 , 0
9499.039    0.06       09499.039    0.06       010500.97    0.06       0
#XS Ineff= 2 , 0
       0                               0
Bank Sta=9499.039,10500.97
Exp/Cntr=0.3,0.1

Type RM Length L Ch R = 1 ,7373.605,245.253600,245.253600,245.253600
XS GIS Cut Line= 6
604186.947839417794122.050755029604516.259116276 794267.56904721
604580.818843624794304.961416604604678.459552478794376.182199416
604746.982242692794418.173144019605075.153689876794580.113734807
#Sta/Elev= 30
9499.0721657.2579507.8381654.9329540.4981655.9729584.0451663.7329633.0151683.848
9638.4791684.8229660.2531680.7939692.9131672.012  9703.8 1666.719769.382 1620.05
9835.6581585.439 9857.751570.897 9893.921553.4159975.9861531.10310013.131529.283
10025.521530.44310050.321545.793   100741546.25710085.731550.567 10128.91554.256
10155.251559.04810200.291575.188 10256.51585.198 10267.61589.16510300.911603.848
10400.851655.19310411.951658.36210445.261679.01110489.191695.03110500.951704.569
#Mann= 3 , 0 , 0
9499.072    0.04       09499.072    0.04       010500.95    0.04       0
#XS Ineff= 2 , 0
       0                               0
Bank Sta=9499.072,10500.95
Exp/Cntr=0.3,0.1

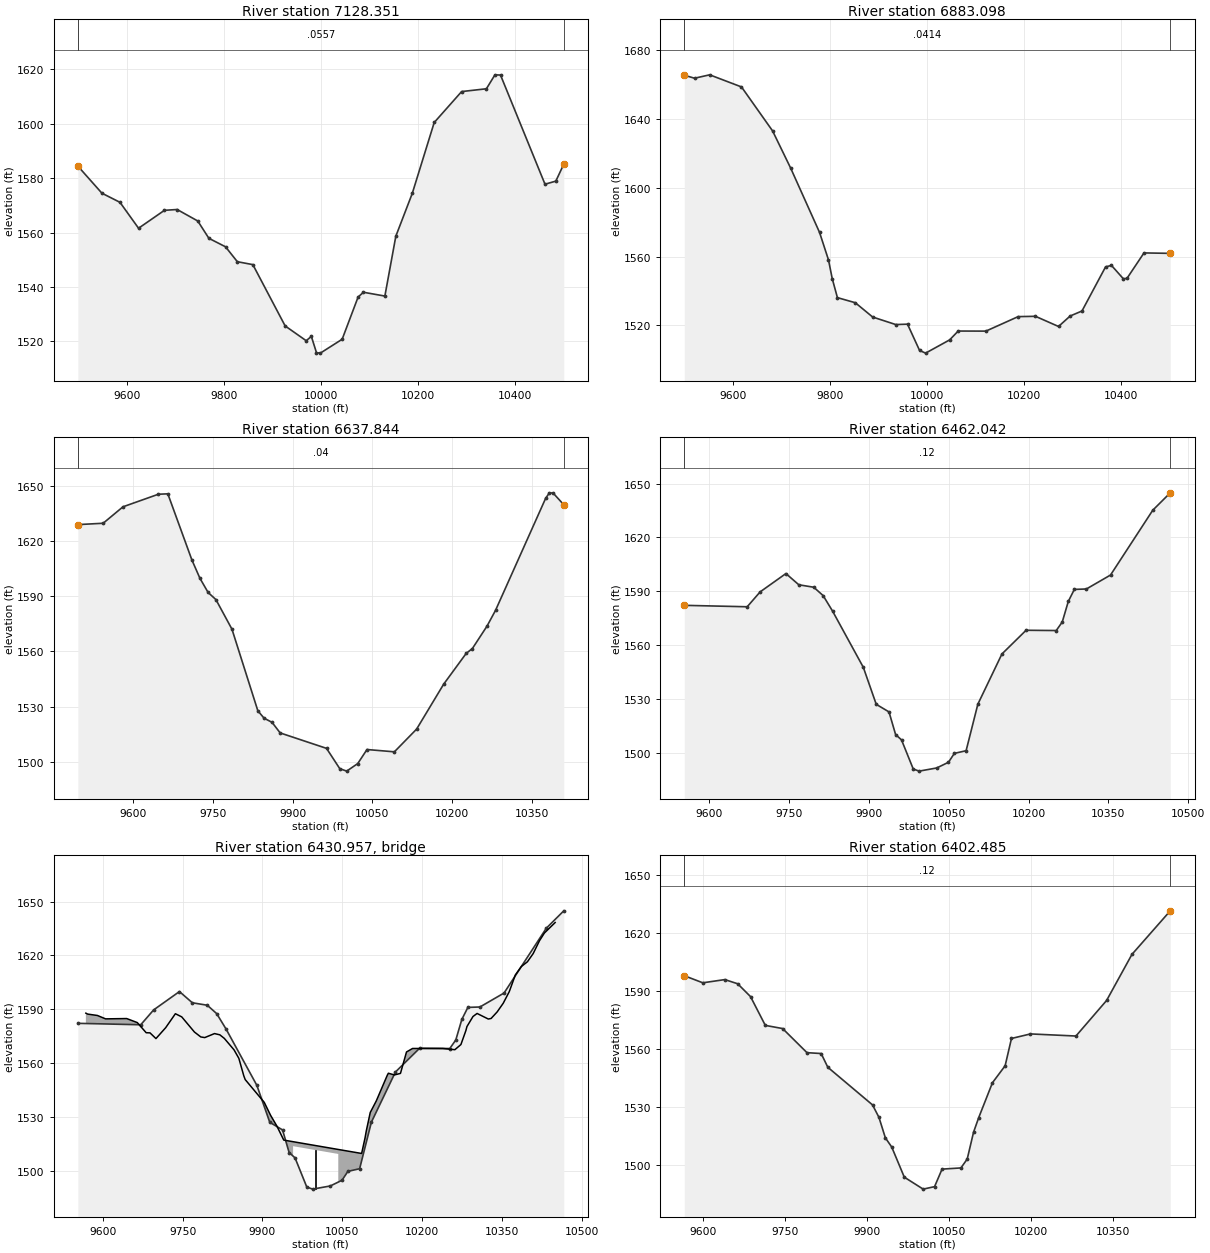
Type RM Length L Ch R = 1 ,7128.351,245.253700,245.253700,245.253700
XS GIS Cut Line= 6
604073.096703726 794318.44253056 604217.62131589794408.119000099
604343.070870758794478.138187328604456.978566096794533.971161771
604627.730019217794602.535805978604958.794187519794783.036569238
#Sta/Elev= 30
9499.0321584.4369548.6591574.473 9585.931571.1169624.2161561.591 9677.581568.178
9703.7671568.4789746.2941564.2559769.1981557.8919803.5551554.7689827.8951549.291
 9859.871548.2189926.4611525.6839969.8671520.2499980.4971521.8359991.0421515.858
    99991515.687   100441520.788 10076.91536.31210087.891538.05910132.07 1536.66
10154.671558.66610188.581574.406 10233.81600.46110290.311611.829 10341.41612.854
10359.021617.98110370.49  1617.910462.211577.77410484.521578.91110500.951585.143
#Mann= 3 , 0 , 0
9499.032  0.0557       09499.032  0.0557       010500.95  0.0557       0
#XS Ineff= 2 , 0
       0                               0
Bank Sta=9499.032,10500.95
Exp/Cntr=0.3,0.1

Type RM Length L Ch R = 1 ,6883.098,245.253600,245.253600,245.253600
XS GIS Cut Line= 6
603995.126327703794471.354633269604099.620979721794560.109013764
604209.592447813794642.704591592604438.054389336794797.747816384
604637.623414128794923.134598379604814.549736614795045.870557705
#Sta/Elev= 30
9499.0541665.4779520.1321663.7189551.3691665.6959616.9711658.6539681.0591633.096
9718.6071611.3049777.9331574.0629796.3271558.0959803.982 1547.299814.722 1536.17
9851.6391533.2059887.3821524.8939935.0391520.5169959.2571520.742 9984.131505.466
9996.5671503.90910046.151511.61310063.741516.74910120.871516.70510187.34 1525.13
10223.031525.31510270.611519.39910294.61  1525.510318.951528.39610367.63 1554.07
 10379.81554.88910404.14 1547.1710411.711547.354 10446.81562.16410500.961561.908
#Mann= 3 , 0 , 0
9499.054  0.0414       09499.054  0.0414       010500.96  0.0414       0
#XS Ineff= 2 , 0
       0                               0
Bank Sta=9499.054,10500.96
Exp/Cntr=0.3,0.1

Type RM Length L Ch R = 1 ,6637.844,175.801500,175.801500,175.801500
XS GIS Cut Line= 6
 603943.96805236794590.598768392604192.003575174794872.932518741
604310.764838157 795024.11038492604354.212393212795076.246652038
604417.247210469795146.566859212604543.931953077795279.269050975
#Sta/Elev= 30
9496.0031628.9539543.6251629.6919580.9061638.6369647.4551645.4679665.2351645.695
9710.4721609.7569725.5511599.7989740.979 1592.069755.7091588.1749785.8671572.078
9834.5031527.7389846.1831523.7139861.2251521.4359876.5391515.6759963.7011507.287
9988.6121496.24610001.66 1494.9110022.421499.02710039.811506.65910091.311505.405
10133.171517.78210184.031542.20510226.421558.94410238.011561.57610265.491573.746
10281.481582.29710375.851643.292 10382.91646.23510389.88 1646.11 10409.91639.747
#Mann= 3 , 0 , 0
9496.003    0.04       09496.003    0.04       0 10409.9    0.04       0
#XS Ineff= 2 , 0
       0                               0
Bank Sta=9496.003,10409.9
Exp/Cntr=0.3,0.1

Type RM Length L Ch R = 1 ,6462.042,59.557600,59.557600,59.557600
XS GIS Cut Line= 4
 603867.43769601794677.507854834 604092.43769601795005.632854834
604159.104362667795148.341188163604327.854362667795463.966188148
#Sta/Elev= 30
9552.9771582.1869671.1881581.3889695.4391589.6699743.9391599.888 9768.191593.633
9796.2231592.2729813.9051587.6059831.5881578.9869889.4421547.6349913.6921527.047
9937.6831522.8129950.0681510.2099961.1741507.2399983.2491491.0049994.2861489.829
 10027.41491.59310049.471494.76810060.511499.71610082.581501.20110104.661527.124
10149.921555.09410195.281568.29510251.971568.14710263.31 1572.9210274.651584.376
10285.991591.06210308.671591.29610354.031599.07810433.411635.18110466.251644.861
#Mann= 3 , 0 , 0
9552.977    0.12       09552.977    0.12       010466.25    0.12       0
#XS Ineff= 2 , 0
       0                               0
Bank Sta=9552.977,10466.25
Exp/Cntr=0.3,0.1

Type RM Length L Ch R = 3 ,6430.957,,,
BEGIN DESCRIPTION:
END DESCRIPTION:
Bridge Culvert--1,0,-1,-1, 0
Deck Dist Width WeirC Skew NumUp NumDn MinLoCord MaxHiCord MaxSubmerge Is_Ogee
24.778800,10.000000,2.6,0, 60, 60, , , 0.95, 0, 0,0,,
 9568.07 9571.37 9589.71 9605.09 9644.74 9664.73 9681.43 9688.58 9699.77 9718.11
 9736.30 9748.23 9772.08 9784.01 9791.49 9809.83 9819.80 9828.18 9846.52 9855.58
 9864.86 9867.51 9903.29 9915.22 9927.15 9940.00 9957.50 9957.5010042.5010042.50
10086.3110092.7210095.0210102.5010113.8610134.6710136.5810147.9410159.3010170.66
10182.0210238.8210261.5410272.9010282.2310284.2610295.6210303.3110324.3910329.69
10341.0510352.4110363.7710375.1310386.4910397.8510408.7110420.5710429.7910450.00
 1587.86 1587.34 1586.57 1584.68 1584.85 1582.60 1576.95 1576.88 1573.69 1579.78
 1587.54 1585.78 1577.35 1574.61 1574.25 1576.48 1575.79 1573.82 1567.42 1562.68
 1552.95 1550.85 1538.18 1530.96 1524.89 1517.14 1516.25 1516.25 1511.92 1511.92
 1509.70 1518.34 1522.18 1532.52 1538.97 1553.36 1554.39 1553.44 1554.30 1566.24
 1568.18 1568.18 1567.50 1570.37 1578.13 1580.40 1586.00 1587.69 1584.58 1584.91
 1588.56 1593.37 1599.83 1609.11 1613.84 1616.47 1621.04 1628.21 1632.50 1638.33
  587.86  587.34  586.57  584.68  584.85  582.60  576.95  576.88  573.69  579.78
  587.54  585.78  577.35  574.61  574.25  576.48  575.79  573.82  567.42  562.68
  552.95  550.85  538.18  530.96  524.89  517.14  516.25 1513.75 1509.42  511.92
  509.70  518.34  522.18  532.52  538.97  553.36  554.39  553.44  554.30  566.24
  568.18  568.18  567.50  570.37  578.13  580.40  586.00  587.69  584.58  584.91
  588.56  593.37  599.83  609.11  613.84  616.47  621.04  628.21  632.50  638.33
 9568.07 9571.37 9589.71 9605.09 9644.74 9664.73 9681.43 9688.58 9699.77 9718.11
 9736.30 9748.23 9772.08 9784.01 9791.49 9809.83 9819.80 9828.18 9846.52 9855.58
 9864.86 9867.51 9903.29 9915.22 9927.15 9940.00 9957.50 9957.5010042.5010042.50
10086.3110092.7210095.0210102.5010113.8610134.6710136.5810147.9410159.3010170.66
10182.0210238.8210261.5410272.9010282.2310284.2610295.6210303.3110324.3910329.69
10341.0510352.4110363.7710375.1310386.4910397.8510408.7110420.5710429.7910450.00
 1587.86 1587.34 1586.57 1584.68 1584.85 1582.60 1576.95 1576.88 1573.69 1579.78
 1587.54 1585.78 1577.35 1574.61 1574.25 1576.48 1575.79 1573.82 1567.42 1562.68
 1552.95 1550.85 1538.18 1530.96 1524.89 1517.14 1516.25 1516.25 1511.92 1511.92
 1509.70 1518.34 1522.18 1532.52 1538.97 1553.36 1554.39 1553.44 1554.30 1566.24
 1568.18 1568.18 1567.50 1570.37 1578.13 1580.40 1586.00 1587.69 1584.58 1584.91
 1588.56 1593.37 1599.83 1609.11 1613.84 1616.47 1621.04 1628.21 1632.50 1638.33
  587.86  587.34  586.57  584.68  584.85  582.60  576.95  576.88  573.69  579.78
  587.54  585.78  577.35  574.61  574.25  576.48  575.79  573.82  567.42  562.68
  552.95  550.85  538.18  530.96  524.89  517.14  516.25 1513.75 1509.42  511.92
  509.70  518.34  522.18  532.52  538.97  553.36  554.39  553.44  554.30  566.24
  568.18  568.18  567.50  570.37  578.13  580.40  586.00  587.69  584.58  584.91
  588.56  593.37  599.83  609.11  613.84  616.47  621.04  628.21  632.50  638.33
Pier Skew, UpSta & Num, DnSta & Num=  ,10000.00, 2 ,10000.00, 2 , 0 , 0 , 0 ,,
    2.00    2.00
  514.09 1514.09
    2.00    2.00
  514.09 1514.09
BR Coef=-1 , 0 , 0 ,, 0 ,,,0.8,0,1,0,
WSPro=,,,, 1 ,,,, 0 ,,,, 0 ,,,,-1 ,-1 ,-1 , 0 , 0 , 0 , 0 , 0
BC Design=,, 0 ,, 0 ,,,,,,

Type RM Length L Ch R = 1 ,6402.485,255.148100,255.148100,255.148100
XS GIS Cut Line= 4
603837.229362667794711.882854834 604033.06269601795029.591188163
604121.604362696795184.799521491 604292.43769601795475.424521491
#Sta/Elev= 30
9565.7041597.9369599.5711594.2869639.8481595.9369663.3421593.7849686.8361587.164
9713.9171572.3049745.5721570.6729790.1481558.2269816.0541557.7849828.2641550.688
9910.0311531.2729921.7781524.8599933.5251514.2749945.146 1509.549968.1711493.973
10002.711487.80610023.551489.08610037.251498.12910071.791498.748 10083.3 1503.35
10094.81 1517.1310104.281524.68910129.441542.71210152.641551.46910164.241565.554
10199.041567.90210282.181566.81410338.231585.15210384.631608.93910454.721631.426
#Mann= 3 , 0 , 0
9565.704    0.12       09565.704    0.12       010454.72    0.12       0
#XS Ineff= 2 , 0
       0                               0
Bank Sta=9565.704,10454.72
Exp/Cntr=0.3,0.1