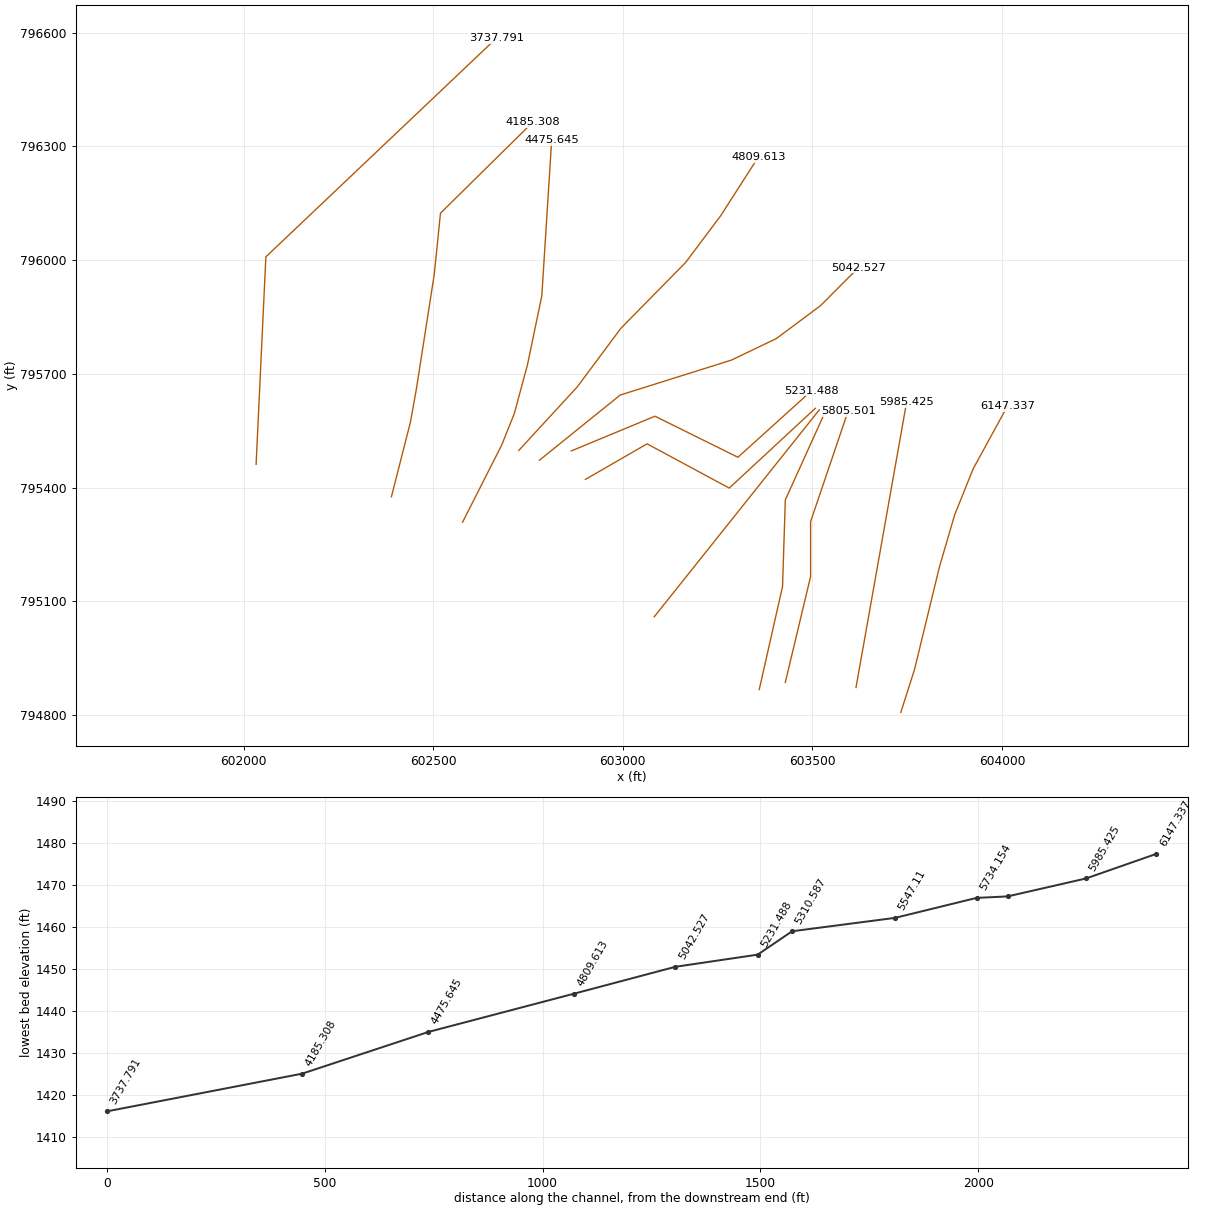
HEC-RAS study 10409_ras.prj: 10409

--- 10409_ras.g01 (geometry) --- (continued)

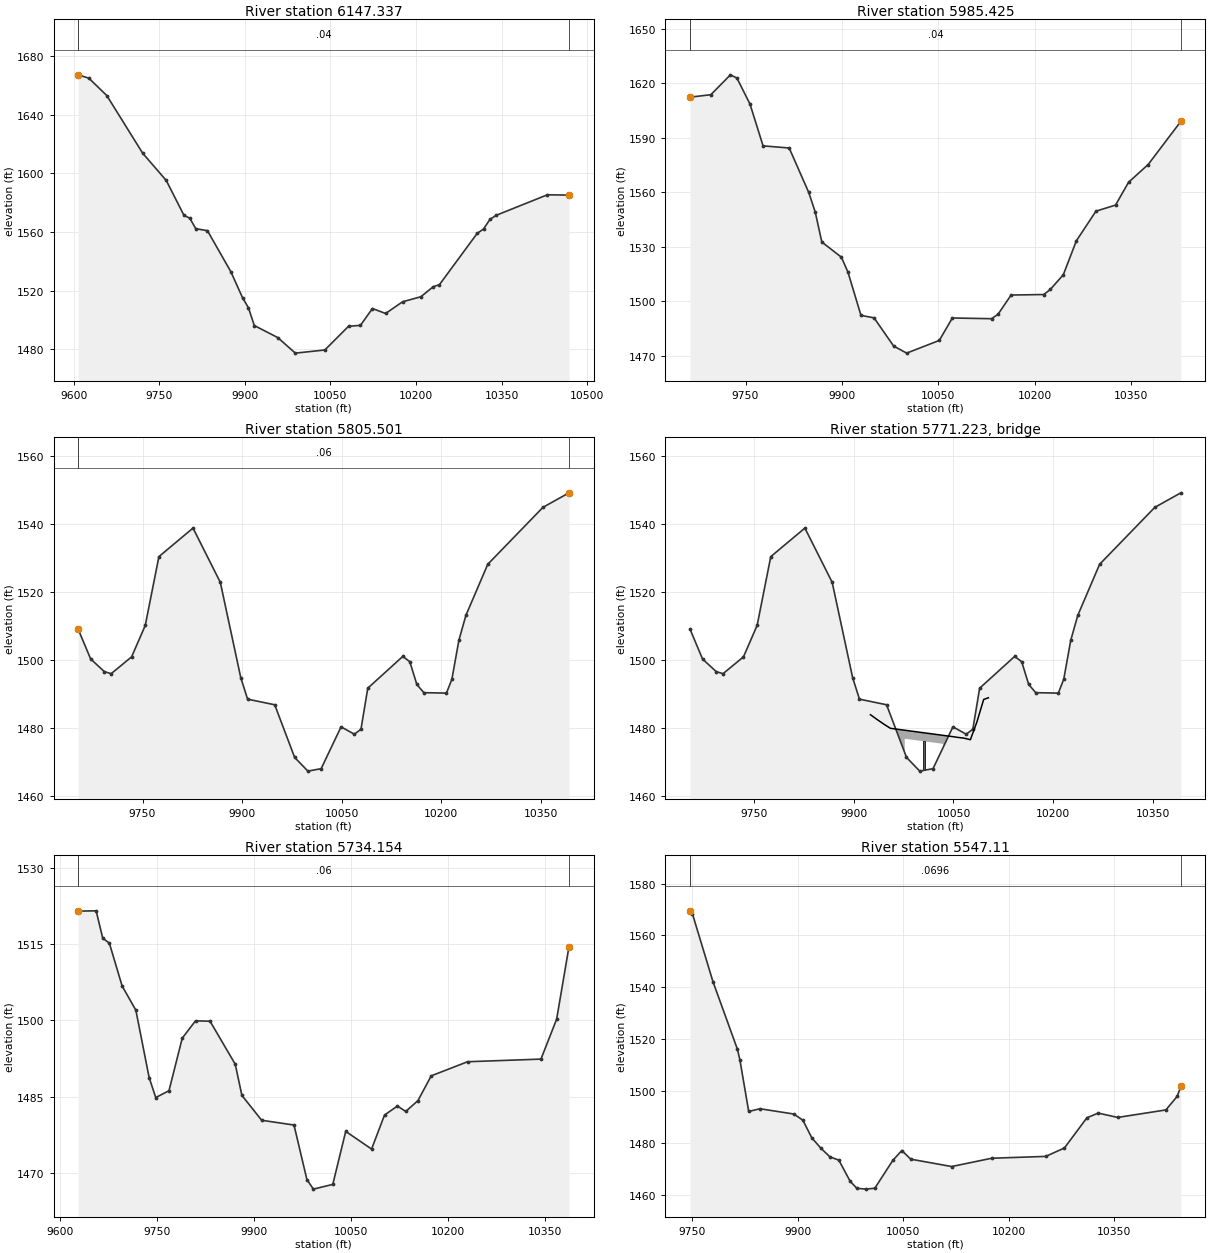
Type RM Length L Ch R = 1 ,6147.337,161.911800,161.911800,161.911800
XS GIS Cut Line= 6
603733.350288954794807.285987401603769.437026875794920.312384745
 603835.45605371795191.989593363603875.506772315795328.721515035
603924.009734384795449.474740061604014.834861595795615.701659798
#Sta/Elev= 30
9607.7041667.3459626.5111665.0769658.0391653.1859720.814  1613.99762.2351595.231
9793.2521571.4599803.5911569.4249813.9221562.343 9834.461560.9419875.5361532.873
9896.074 1515.089906.3431508.2949916.6121496.1899957.6881487.9889988.4951477.358
10040.221479.50410081.721495.67210102.641496.32710123.611507.80810146.791504.432
 10176.51512.41410208.491515.84310230.191522.68110241.091524.08810307.221559.099
10318.411562.10610329.611568.651 10340.81571.48910430.281585.44510468.18 1585.24
#Mann= 3 , 0 , 0
9607.704    0.04       09607.704    0.04       010468.18    0.04       0
#XS Ineff= 2 , 0
       0                               0
Bank Sta=9607.704,10468.18
Exp/Cntr=0.3,0.1

Type RM Length L Ch R = 1 ,5985.425,179.924300,179.924300,179.924300
XS GIS Cut Line= 2
603615.180751562794872.993965954603748.514084905795625.077299267
#Sta/Elev= 30
9663.5211612.3059696.0261613.6669726.494  1624.6 9736.651622.7999756.9621608.484
9777.2741585.5169817.8981584.3529848.3651559.8689858.5211549.0139868.6771532.627
9899.145 1524.279909.3011516.1039929.6131492.2569949.9251490.9119980.3931475.402
 10000.7 1471.4910051.481478.478 10071.81490.82210132.731490.42810142.891492.879
 10163.21503.44910213.98 1503.7310224.141506.50310244.451514.62810264.761533.302
10295.231549.58310325.691552.93910346.011565.52210376.471575.26110427.331598.997
#Mann= 3 , 0 , 0
9663.521    0.04       09663.521    0.04       010427.33    0.04       0
#XS Ineff= 2 , 0
       0                               0
Bank Sta=9663.521,10427.33
Exp/Cntr=0.3,0.1

Type RM Length L Ch R = 1 ,5805.501,71.347100,71.347100,71.347100
XS GIS Cut Line= 4
603428.722418219794886.535632595603495.389084905795165.702299282
603495.389084905795310.493965939603594.347418249 795602.16063261
#Sta/Elev= 30
9652.8721509.0379671.8561500.2089692.4181496.5079702.6991495.8889733.5431500.844
9754.1051510.0869774.6681530.3269826.0741538.7239867.1981522.7679898.0421494.711
9908.3231488.3939949.1861486.7459979.1861471.2739999.1861467.22310019.19 1467.95
10049.191480.25510069.191478.08210079.191479.56110089.441491.62310142.241500.976
 10152.81499.40810163.361492.72310173.921490.30410207.971490.17210216.161494.232
10226.721505.69810237.281513.02610270.211528.06510353.441544.82710392.681549.095
#Mann= 3 , 0 , 0
9652.872    0.06       09652.872    0.06       010392.68    0.06       0
#XS Ineff= 2 , 0
       0                               0
Bank Sta=9652.872,10392.68
Exp/Cntr=0.3,0.1

Type RM Length L Ch R = 3 ,5771.223,,,
BEGIN DESCRIPTION:
END DESCRIPTION:
Bridge Culvert--1,0,-1,-1, 0
Deck Dist Width WeirC Skew NumUp NumDn MinLoCord MaxHiCord MaxSubmerge Is_Ogee
19.925550,31.496000,2.6,0, 16, 16, , , 0.95, 0, 0,0,,
 9924.78 9925.47 9935.47 9945.47 9954.94 9976.63 9976.6310034.7010034.7010052.17
10055.4810065.4910075.4910085.4910095.4910102.58
 1483.81 1483.74 1482.33 1480.99 1479.82 1479.25 1479.25 1477.74 1477.74 1477.28
 1477.17 1476.94 1476.47 1481.79 1488.30 1488.81
  483.81  483.74  482.33  480.99  479.82  479.25 1476.75 1475.24  477.74  477.28
  477.17  476.94  476.47  481.79  488.30  488.81
 9924.78 9925.47 9935.47 9945.47 9954.94 9972.80 9972.8010030.8710030.8710052.17
10055.4810065.4910075.4910085.4910095.4910102.58
 1483.81 1483.74 1482.33 1480.99 1479.82 1479.35 1479.35 1477.84 1477.84 1477.28
 1477.17 1476.94 1476.47 1481.79 1488.30 1488.81
  483.81  483.74  482.33  480.99  479.82  479.35 1476.85 1475.34  477.84  477.28
  477.17  476.94  476.47  481.79  488.30  488.81
Pier Skew, UpSta & Num, DnSta & Num=  ,10005.66, 2 ,10001.84, 2 , 0 , 0 , 0 ,,
    3.00    3.00
  478.49 1478.49
    3.00    3.00
  478.59 1478.59
BR Coef=-1 , 0 , 0 ,, 0 ,,,0.8,0,1,0,
WSPro=,,,, 1 ,,,, 0 ,,,, 0 ,,,,-1 ,-1 ,-1 , 0 , 0 , 0 , 0 , 0
BC Design=,, 0 ,, 0 ,,,,,,

Type RM Length L Ch R = 1 ,5734.154,187.043800,187.043800,187.043800
XS GIS Cut Line= 4
603359.972418219794867.785632595603421.430751592 795139.66063261
603428.722418219 795367.78563261603532.889084905795597.993965939
#Sta/Elev= 30
9627.899 1521.44  9655.81521.4999666.0531516.1369676.3051515.1469696.055 1506.74
9717.3141501.9859737.8191488.7749748.0711484.8339768.5761486.191 9789.081496.499
9809.5851499.9039832.1151499.8289871.0991491.3789881.3511485.2719911.9761480.381
9962.0021479.4479982.0121468.7289992.0171466.86310022.031467.79210042.041478.199
10082.061474.72910102.07  1481.410122.081483.18110134.881482.11510153.771484.235
10174.361489.105 10230.61491.87310344.161492.38910368.421500.22910387.551514.476
#Mann= 3 , 0 , 0
9627.899    0.06       09627.899    0.06       010387.55    0.06       0
#XS Ineff= 2 , 0
       0                               0
Bank Sta=9627.899,10387.55
Exp/Cntr=0.3,0.1

Type RM Length L Ch R = 1 , 5547.11,236.523000,236.523000,236.523000
XS GIS Cut Line= 2
603082.889084935795059.452299282603518.305751562 795605.28563261
#Sta/Elev= 30
 9746.391569.5119749.7751568.4689779.0711542.2139813.9191516.0669817.4471511.945
9829.9541492.083 9845.991493.1339894.1981491.088 9906.991488.7039919.7821481.866
9932.5741477.9169945.3661474.5849958.1581473.2899974.2771465.1319983.7421462.454
9996.534 1462.1110009.33 1462.4510034.911473.208 10047.71477.00910060.491473.668
 10118.61470.82610175.621474.03510252.371474.73910278.961477.98210311.031489.658
10327.071491.45210354.711489.77610423.281492.67510439.32  1497.910444.621501.717
#Mann= 3 , 0 , 0
 9746.39  0.0696       0 9746.39  0.0696       010444.62  0.0696       0
#XS Ineff= 2 , 0
       0                               0
Bank Sta=9746.39,10444.62
Exp/Cntr=0.3,0.1

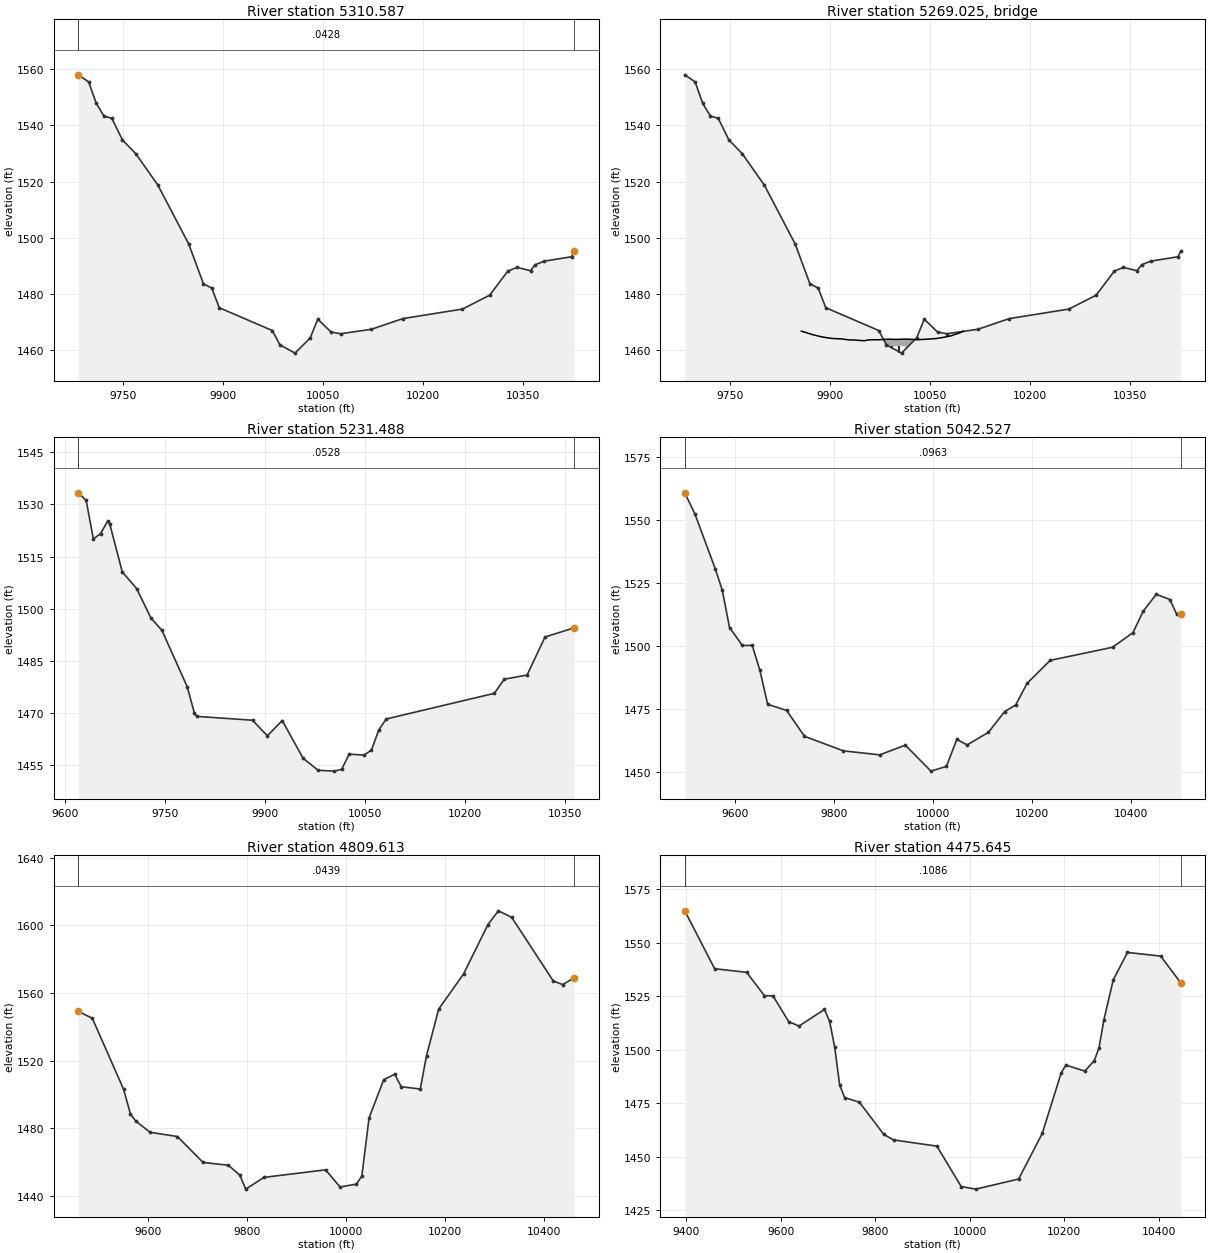
Type RM Length L Ch R = 1 ,5310.587,79.098700,79.098700,79.098700
XS GIS Cut Line= 4
602901.639084935795421.952299282603064.139084935795515.702299267
603280.805751592 795399.03563261603507.889084905795609.452299267
#Sta/Elev= 30
9682.7661558.0159698.1911555.4999709.7361547.8079721.2811543.3049732.8251542.553
9748.8981534.8369768.9091529.9259802.0951518.7129848.2741497.759 9870.371483.583
9882.7051482.1159894.063 1475.099973.5661466.9649984.9231461.86910007.641458.922
10030.35 1464.3410041.711471.00610061.68 1466.4310075.781465.81810122.171467.418
10169.361471.229 10258.51474.603 10299.41479.55710326.661488.136 10340.31489.437
10360.631488.26410367.561490.395 10381.2 1491.67 10422.11493.23610426.03 1495.17
#Mann= 3 , 0 , 0
9682.766  0.0428       09682.766  0.0428       010426.03  0.0428       0
#XS Ineff= 2 , 0
       0                               0
Bank Sta=9682.766,10426.03
Exp/Cntr=0.3,0.1

Type RM Length L Ch R = 3 ,5269.025,,,
BEGIN DESCRIPTION:
END DESCRIPTION:
Bridge Culvert--1,0,-1,-1, 0
Deck Dist Width WeirC Skew NumUp NumDn MinLoCord MaxHiCord MaxSubmerge Is_Ogee
30.034950,19.028800,2.6,0, 43, 43, , , 0.95, 0, 0,0,,
 9857.46 9862.87 9866.72 9873.92 9884.97 9890.23 9896.01 9903.49 9907.13 9913.03
 9918.37 9929.61 9934.91 9940.86 9952.10 9956.79 9958.54 9963.60 9975.45 9975.68
 9982.44 9982.44 9987.31 9994.31 9999.1610011.0110012.9410013.6110013.6110022.86
10031.5710034.7210046.5710047.5010050.1110058.5710058.6510067.9210070.7210082.87
10085.5210095.0210100.15
 1466.76 1466.36 1466.09 1465.53 1464.88 1464.63 1464.40 1464.16 1464.09 1464.03
 1463.98 1463.60 1463.63 1463.52 1463.33 1463.60 1463.62 1463.68 1463.70 1463.73
 1463.81 1463.81 1463.88 1463.84 1463.82 1463.88 1463.91 1463.90 1463.90 1463.83
 1463.74 1463.73 1463.90 1463.91 1463.96 1464.09 1464.09 1464.43 1464.56 1465.12
 1465.40 1466.13 1466.74
  466.76  466.36  466.09  465.53  464.88  464.63  464.40  464.16  464.09  464.03
  463.98  463.60  463.63  463.52  463.33  463.60  463.62  463.68  463.70  463.73
  463.81 1461.31 1461.38 1461.34 1461.32 1461.38 1461.41 1461.40  463.90  463.83
  463.74  463.73  463.90  463.91  463.96  464.09  464.09  464.43  464.56  465.12
  465.40  466.13  466.74
 9857.46 9862.87 9866.72 9873.92 9884.97 9890.23 9896.01 9903.49 9907.13 9913.03
 9918.37 9929.61 9934.91 9940.86 9952.10 9956.79 9958.54 9963.60 9975.45 9975.68
 9986.77 9986.77 9987.31 9994.31 9999.1610011.0110012.9410017.9410017.9410022.86
10031.5710034.7210046.5710047.5010050.1110058.5710058.6510067.9210070.7210082.87
10085.5210095.0210100.15
 1466.76 1466.36 1466.09 1465.53 1464.88 1464.63 1464.40 1464.16 1464.09 1464.03
 1463.98 1463.60 1463.63 1463.52 1463.33 1463.60 1463.62 1463.68 1463.70 1463.73
 1463.87 1463.87 1463.88 1463.84 1463.82 1463.88 1463.91 1463.87 1463.87 1463.83
 1463.74 1463.73 1463.90 1463.91 1463.96 1464.09 1464.09 1464.43 1464.56 1465.12
 1465.40 1466.13 1466.74
  466.76  466.36  466.09  465.53  464.88  464.63  464.40  464.16  464.09  464.03
  463.98  463.60  463.63  463.52  463.33  463.60  463.62  463.68  463.70  463.73
  463.87 1461.37 1461.38 1461.34 1461.32 1461.38 1461.41 1461.37  463.87  463.83
  463.74  463.73  463.90  463.91  463.96  464.09  464.09  464.43  464.56  465.12
  465.40  466.13  466.74
Pier Skew, UpSta & Num, DnSta & Num=  ,9992.50, 2 ,9996.83, 2 , 0 , 0 , 0 ,,
    2.00    2.00
  463.85 1463.85
    2.00    2.00
  463.83 1463.83
Pier Skew, UpSta & Num, DnSta & Num=  ,10003.56, 2 ,10007.88, 2 , 0 , 0 , 0 ,,
    2.00    2.00
  463.84 1463.84
    2.00    2.00
  463.87 1463.87
BR Coef=-1 , 0 , 0 ,, 0 ,,,0.8,0,1,0,
WSPro=,,,, 1 ,,,, 0 ,,,, 0 ,,,,-1 ,-1 ,-1 , 0 , 0 , 0 , 0 , 0
BC Design=,, 0 ,, 0 ,,,,,,

Type RM Length L Ch R = 1 ,5231.488,188.960800,188.960800,188.960800
XS GIS Cut Line= 4
602864.139084935795496.952299267603084.972418219795588.618965939
603303.722418219 795480.28563261603497.472418219 795655.28563261
#Sta/Elev= 30
9619.8571533.3519631.6161531.1669642.4431520.1029653.2711521.6319664.0981525.306
9666.9321524.4689685.7521510.6579707.4071505.8169729.0621497.3039745.184 1493.87
9783.1981477.6649794.0251470.0929797.3521469.0959881.308 1467.989903.6271463.512
9925.9451467.8969957.2451457.0559979.7781453.60110004.061453.35110015.221453.869
10026.381458.245 10048.71457.96110059.851459.39710071.011465.25510082.171468.347
10244.371475.71810259.291479.78610293.441480.96510320.391491.90410364.151494.548
#Mann= 3 , 0 , 0
9619.857  0.0528       09619.857  0.0528       010364.15  0.0528       0
#XS Ineff= 2 , 0
       0                               0
Bank Sta=9619.857,10364.15
Exp/Cntr=0.3,0.1

Type RM Length L Ch R = 1 ,5042.527,232.914600,232.914600,232.914600
XS GIS Cut Line= 6
602780.220806771795472.546652792602993.208921531795644.416676194
  603286.5186827795736.556073213603405.149152873795793.432261998
603521.894961806 795880.44569554603621.878547126795980.739193014
#Sta/Elev= 30
9499.1021560.7849519.5521552.3969560.5221530.749 9574.991522.0789589.4571507.361
9615.4741500.2729635.3641500.2989650.9311490.3529666.4981476.958 9704.791474.519
9740.9291464.2699819.6021458.4949893.0341456.9159944.7071460.768 9996.38 1450.46
10027.731452.34710048.691463.04310069.651460.84110112.651465.85610145.231474.062
10167.741476.68510190.511485.22410237.311494.36310363.461499.57210404.721505.388
10425.141513.84310451.681520.55310479.211518.48310492.971512.60510500.871512.799
#Mann= 3 , 0 , 0
9499.102  0.0963       09499.102  0.0963       010500.87  0.0963       0
#XS Ineff= 2 , 0
       0                               0
Bank Sta=9499.102,10500.87
Exp/Cntr=0.3,0.1

Type RM Length L Ch R = 1 ,4809.613,333.967800,333.967800,333.967800
XS GIS Cut Line= 6
602725.685824538795498.303288945602879.628198054795665.552350628
602995.279221799795820.751142202603165.731490362795994.027183369
603258.281503919796117.376260329603357.241034126796271.696711055
#Sta/Elev= 30
9459.422 1549.119487.6161545.0569550.9741503.009  9564.71488.4639575.2031484.335
9604.3991477.6649659.616 1475.149711.3951459.8559762.5661458.156 9785.481452.448
9797.6941444.0539834.447 1450.999959.0711455.4629988.2931445.30410021.341447.024
10032.281451.77710046.911486.14210076.541508.76710098.671511.96510111.841504.625
10150.341503.20610163.031522.97210187.561550.45410237.981571.30810287.131600.427
 10308.21608.55910335.151604.71110419.061567.13210438.061564.94810461.331568.994
#Mann= 3 , 0 , 0
9459.422  0.0439       09459.422  0.0439       010461.33  0.0439       0
#XS Ineff= 2 , 0
       0                               0
Bank Sta=9459.422,10461.33
Exp/Cntr=0.3,0.1

Type RM Length L Ch R = 1 ,4475.645,290.337200,290.337200,290.337200
XS GIS Cut Line= 6
602577.460229492795309.104969667602680.407766184 795511.92349391
602713.917220029795595.688890539602748.517603782795723.731457412
602786.460528515795906.173351692602812.491795921796316.951060691
#Sta/Elev= 30
  9397.3  1564.8 9460.381537.7919528.0941536.0939565.8011525.1949583.8691525.082
9617.1121513.1029638.868 1511.05 9692.721518.784 9703.491513.2189714.2611501.315
 9724.741483.6639735.1981477.6919766.5721475.517 9818.211460.4779838.748 1457.92
9930.4961455.0099981.7561436.16710012.691434.95510103.231439.65810153.271460.931
 10193.31489.19510203.311492.82310243.351490.02210263.361494.95310273.37 1500.92
10283.381513.68410303.391532.587 10333.51545.38710403.771543.67310445.891531.276
#Mann= 3 , 0 , 0
  9397.3  0.1086       0  9397.3  0.1086       010445.89  0.1086       0
#XS Ineff= 2 , 0
       0                               0
Bank Sta=9397.3,10445.89
Exp/Cntr=0.3,0.1

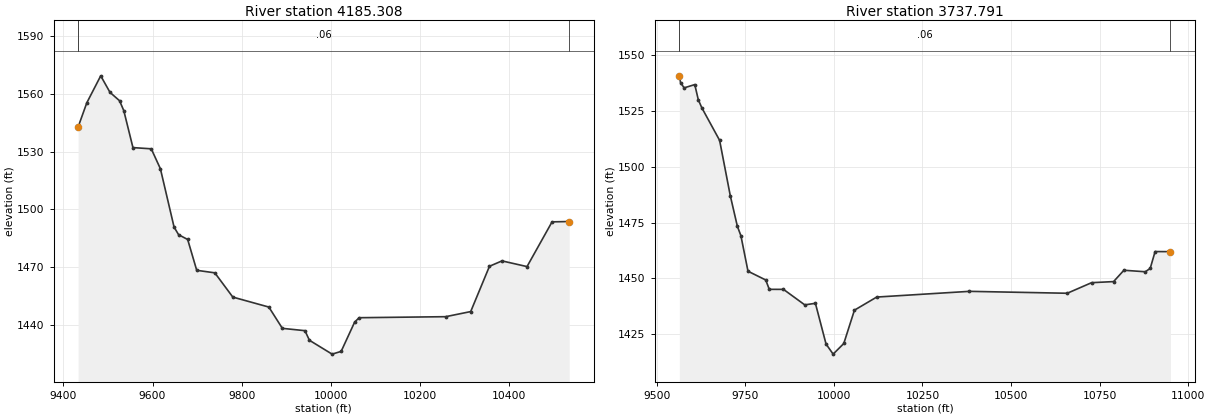
Type RM Length L Ch R = 1 ,4185.308,447.516900,447.516900,447.516900
XS GIS Cut Line= 6
602389.795542568 795376.21523419602439.929003298  795572.9769146
602455.857282788795661.799264893602502.861993551795963.171519652
602519.175489634796124.133515984 602762.36980617796363.778726295
#Sta/Elev= 30
9433.0191542.7249452.564 1555.319483.7791569.2929504.5881560.7199526.0651556.365
9535.5411551.2419556.074 1532.089597.1411531.4539617.6751521.1029648.3461490.856
9658.5061486.9099678.8251484.4469699.1441468.4629739.7071467.1579780.1171454.576
9860.937 1449.419891.2441438.3759941.8621437.1679952.0131432.185 10002.81425.009
10023.121426.42310053.45 1441.6310063.531443.888 10257.61444.41910313.761447.073
10355.871470.56410383.951473.34110440.111470.39410496.271493.58510534.691493.754
#Mann= 3 , 0 , 0
9433.019    0.06       09433.019    0.06       010534.69    0.06       0
#XS Ineff= 2 , 0
       0                               0
Bank Sta=9433.019,10534.69
Exp/Cntr=0.3,0.1

Type RM Length L Ch R = 1 ,3737.791,97.782000,97.782000,97.782000
XS GIS Cut Line= 3
602032.889084905795461.535632625602058.628299177796008.922921911
602666.391514093796585.394272014
#Sta/Elev= 30
9564.173 1540.879567.6411537.7949577.652 1535.479607.6851536.9389617.6961530.101
9627.7071526.4939677.7631511.9389707.7961487.1779727.8181473.4129737.8291469.171
9757.8511453.2379807.9061449.3049817.9171445.1059857.9611445.0979918.0281438.147
9948.0611438.8429978.0941420.5779998.1161416.05210028.151420.81910058.181435.764
10120.951441.64610382.82 1444.2110658.641443.35110727.391448.09710789.421448.583
10818.491453.67110879.011452.99310892.791454.52110906.571462.05310949.841462.012
#Mann= 3 , 0 , 0
9564.173    0.06       09564.173    0.06       010949.84    0.06       0
#XS Ineff= 2 , 0
       0                               0
Bank Sta=9564.173,10949.84
Exp/Cntr=0.3,0.1