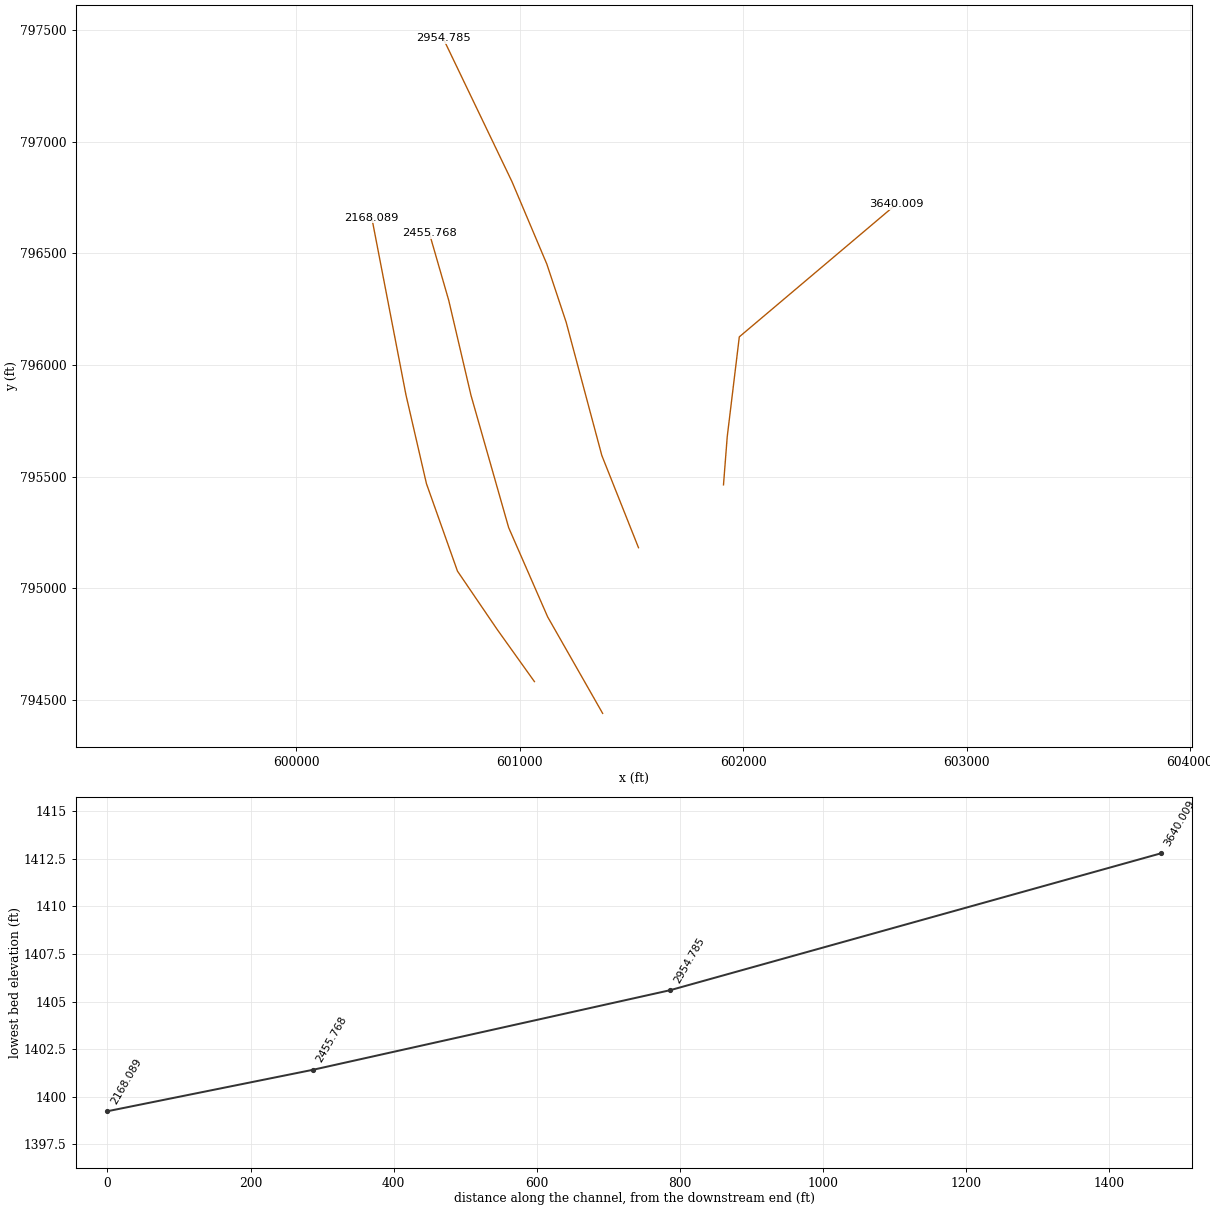
HEC-RAS study 10409_ras.prj: 10409

--- 10409_ras.g01 (geometry) --- (continued)

Type RM Length L Ch R = 3 ,3697.457,,,
BEGIN DESCRIPTION:
END DESCRIPTION:
Bridge Culvert--1,0,-1,-1, 0
Deck Dist Width WeirC Skew NumUp NumDn MinLoCord MaxHiCord MaxSubmerge Is_Ogee
31.174500,35.433000,2.6,0, 19, 19, , , 0.95, 0, 0,0,,
 9919.68 9921.48 9926.53 9936.58 9946.64 9954.49 9959.81 9959.8110058.5610058.56
10071.0810077.3210087.3810097.4310107.4810116.6810117.5310127.5910133.50
 1435.23 1435.16 1435.00 1435.60 1435.74 1435.91 1435.98 1435.98 1437.28 1437.28
 1437.44 1437.47 1437.67 1437.86 1438.05 1438.10 1438.11 1438.25 1438.38
  435.23  435.16  435.00  435.60  435.74  435.91  435.98 1432.98 1434.28  437.28
  437.44  437.47  437.67  437.86  438.05  438.10  438.11  438.25  438.38
 9919.68 9921.48 9926.53 9936.58 9946.64 9954.49 9963.78 9963.7810062.5310062.53
10071.0810077.3210087.3810097.4310107.4810116.6810117.5310127.5910133.50
 1435.23 1435.16 1435.00 1435.60 1435.74 1435.91 1436.03 1436.03 1437.33 1437.33
 1437.44 1437.47 1437.67 1437.86 1438.05 1438.10 1438.11 1438.25 1438.38
  435.23  435.16  435.00  435.60  435.74  435.91  436.03 1433.03 1434.33  437.33
  437.44  437.47  437.67  437.86  438.05  438.10  438.11  438.25  438.38
Pier Skew, UpSta & Num, DnSta & Num=  ,10009.19, 2 ,10013.16, 2 , 0 , 0 , 0 ,,
    3.00    3.00
  436.63 1436.63
    3.00    3.00
  436.68 1436.68
BR Coef=-1 , 0 , 0 ,, 0 ,,,0.8,0,1,0,
WSPro=,,,, 1 ,,,, 0 ,,,, 0 ,,,,-1 ,-1 ,-1 , 0 , 0 , 0 , 0 , 0
BC Design=,, 0 ,, 0 ,,,,,,

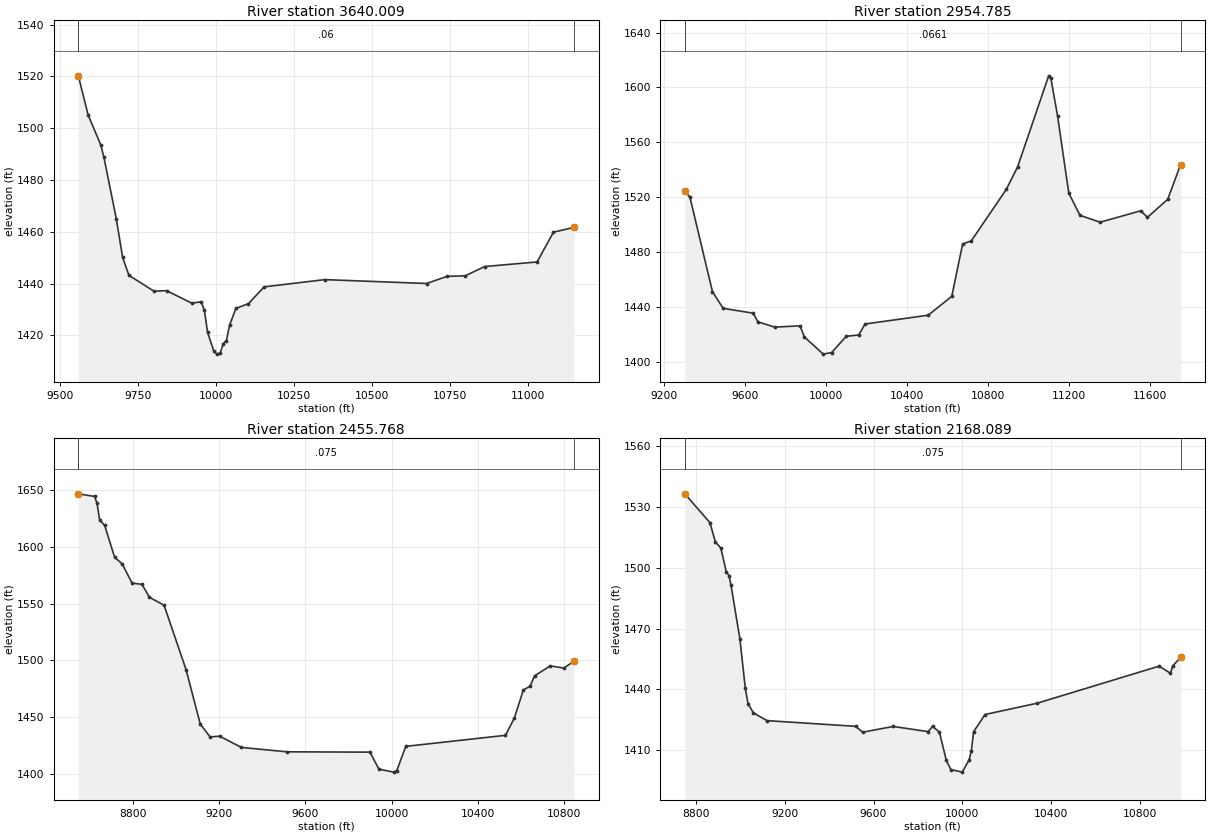
Type RM Length L Ch R = 1 ,3640.009,685.224000,685.224000,685.224000
XS GIS Cut Line= 5
601912.055751562795463.618965954601928.722418249795678.202299282
601977.010455161796077.507219911601982.889084935796126.118965954
602685.606129229 796719.89657785
#Sta/Elev= 30
9559.9361520.2459591.4111505.0699631.5321493.6299641.5621488.9439681.6821464.832
9701.7431450.0979721.8031443.1979802.158 1437.07 9842.451437.2879923.0321432.435
9953.2511433.0059963.3241429.6469973.3971421.2179993.542 1413.8710003.621412.777
10013.691413.18610023.761416.81710033.831418.02510043.911424.00310064.051430.434
10104.341432.28410154.711438.75410348.56 1441.5510674.231440.04810739.691442.804
10797.881443.02610859.861446.60111027.721448.36811080.081459.86811146.341461.737
#Mann= 3 , 0 , 0
9559.936    0.06       09559.936    0.06       011146.34    0.06       0
#XS Ineff= 2 , 0
       0                               0
Bank Sta=9559.936,11146.34
Exp/Cntr=0.3,0.1

Type RM Length L Ch R = 1 ,2954.785,499.016700,499.016700,499.016700
XS GIS Cut Line= 6
601531.634041046795182.353440825601367.451290536795595.172009658
601207.972621712796191.156998809601121.442094318796451.495833354
600965.750648991796819.865443156600657.289200929797462.336633043
#Sta/Elev= 30
9302.1531524.2269327.1891520.1379438.6931451.1639491.3571438.9739641.1721435.422
9662.4411429.169 9746.651425.2839871.5061426.2169892.3151418.1719985.9551405.598
10027.331406.75610099.681418.59710161.421419.56110192.291427.56310504.151433.948
10620.791447.73910674.241485.87510717.181488.14210890.751525.84910945.441541.938
11099.22 1608.4511110.271606.57411143.441578.97911198.711522.91711253.981506.733
11353.871501.76211553.891510.07711587.231505.31111687.25 1518.4711750.961543.812
#Mann= 3 , 0 , 0
9302.153  0.0661       09302.153  0.0661       011750.96  0.0661       0
#XS Ineff= 2 , 0
       0 9863.61        10331.13       0
Bank Sta=9302.153,11750.96
Exp/Cntr=0.3,0.1

Type RM Length L Ch R = 1 ,2455.768,287.679200,287.679200,287.679200
XS GIS Cut Line= 6
601371.153272093794440.720233186601124.994743802794872.692216204
600950.406407028795272.307833324600781.703922449795864.842807262
600682.311151768796289.077474727600595.113978584796591.168065648
#Sta/Elev= 30
8546.6121646.9388621.9071644.6448633.6211638.4538645.3351623.8568668.7621619.086
8714.9951590.9858749.6131585.2568795.7691568.1888841.9251567.068 8876.461555.689
8944.4911548.6289046.4881491.749 9112.261443.829 9157.781432.4969202.1361433.151
9303.3631423.187  9514.81419.3419899.4071419.0459940.8891404.07510009.34 1401.42
10024.071402.84710065.581424.14810528.081433.89610569.541449.26710611.021473.921
10642.141477.22610662.881486.33810735.71 1495.1210798.461493.25410846.741499.184
#Mann= 3 , 0 , 0
8546.612   0.075       08546.612   0.075       010846.74   0.075       0
#XS Ineff= 2 , 0
       0 9744.08        10141.53       0
Bank Sta=8546.612,10846.74
Exp/Cntr=0.3,0.1

Type RM Length L Ch R = 1 ,2168.089,0.000000,0.000000,0.000000
XS GIS Cut Line= 6
601065.736307114794583.017114103600899.069640458794816.350447446
600721.291862667795077.461558536600582.402973771795469.128225222
600490.736307114795866.350447431 600337.59342541 796659.90901624
#Sta/Elev= 30
8749.6881536.4118862.7261522.2558887.3041512.7098911.8821509.715 8936.461498.032
8948.7491496.0898957.411 1491.698997.9051464.9849022.484 1440.469034.7731432.869
9058.9941428.4329119.4831424.6329519.468 1421.819551.2991418.924 9689.231421.752
9845.7471419.2019866.2731421.7939897.061 1418.92 9927.851405.0599948.3751400.518
 9999.691399.24110030.481405.24110040.741409.611   100511419.14110102.321427.635
10337.121433.20210887.081451.48310938.011447.94410948.191451.66410983.741455.747
#Mann= 3 , 0 , 0
8749.688   0.075       08749.688   0.075       010983.74   0.075       0
#XS Ineff= 2 , 0
       09716.102        10119.94       0
Bank Sta=8749.688,10983.74
Exp/Cntr=0.3,0.1